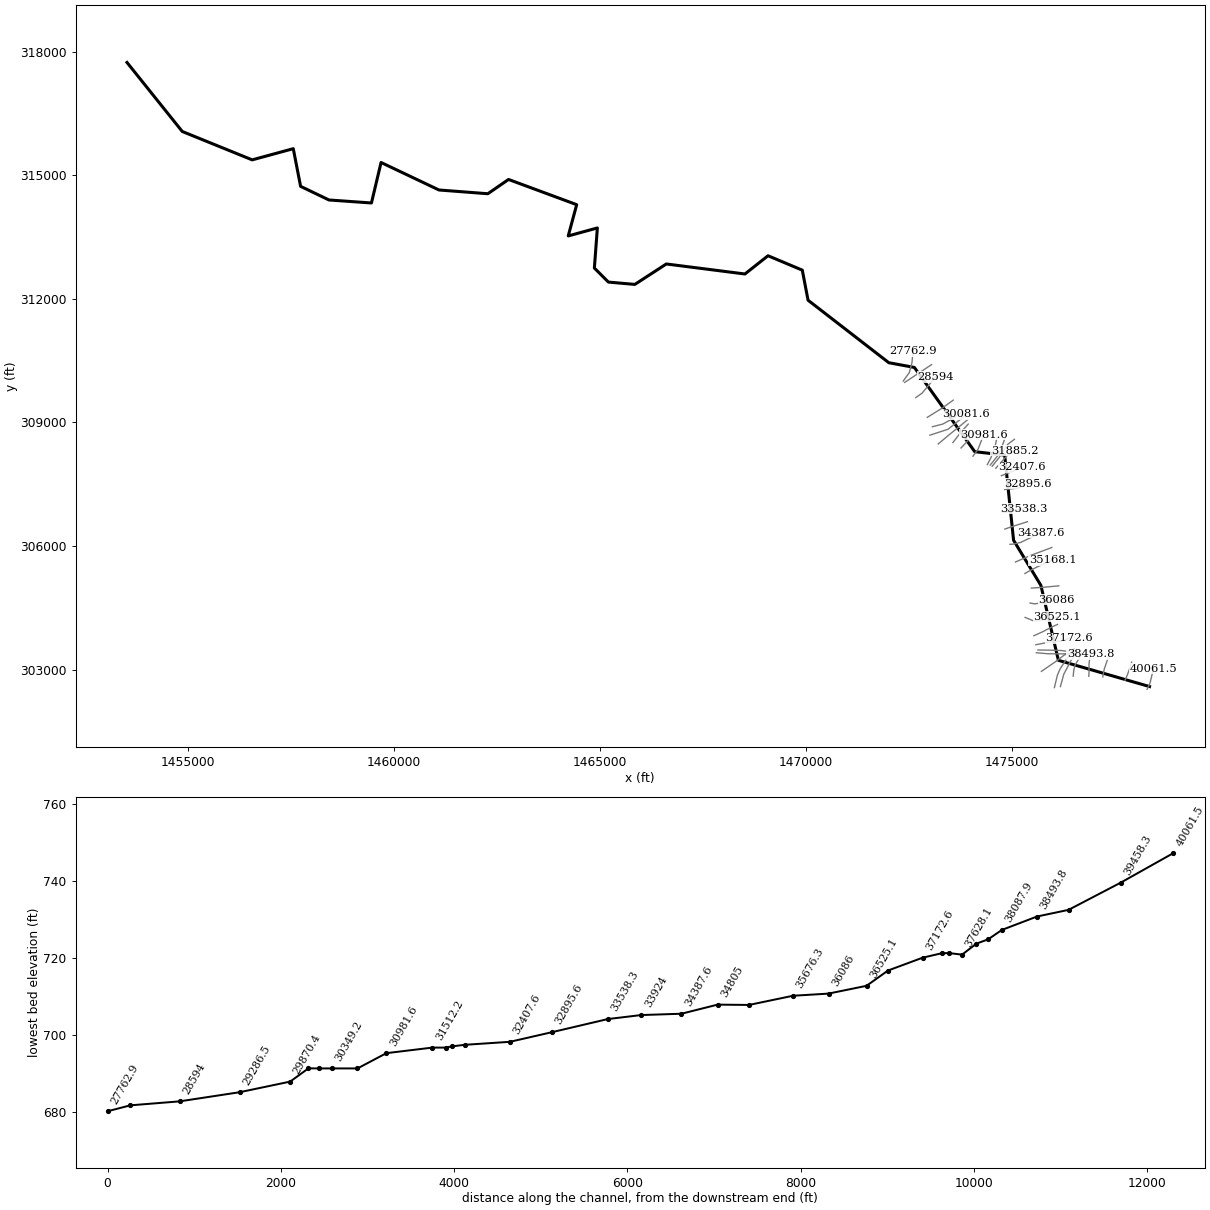
--- CowCr.prj (project) ---

Proj Title=CowCr
Current Plan=p01
Default Exp/Contr=0,0
English Units
Geom File=g01
Flow File=f01
Plan File=p01
BEGIN DESCRIPTION:
END DESCRIPTION:
DSS Export Rating Curves= 0
DSS Export Rating Curve Sorted= 0
DSS Export Volume Flow Curves= 0
DXF OffsetX= 0
DXF OffsetY= 0
DXF ScaleX= 0
DXF ScaleY= 0

--- CowCr.p01 (plan) ---

Plan Title=Floodplain
Program Version=4.00
Geom File=g01
Flow File=f01
K Sum by GR=0
Std Step Tol=0.01
Critical Tol=0.01
Num of Std Step Trials=20
Max Error Tol=0.3
Flow Tol Ratio=0.001
Split Flow NTrial=30
Split Flow Tol=0.02
Split Flow Ratio=0.02
Log Output Level=0
Friction Slope Method=1
Unsteady Friction Slope Method=2
Unsteady Bridges Friction Slope Method=1
Global Log Level=0
CheckData=False
Run HTab=0
Run UNet=0
Run PostProcess=0
UNET Theta=0
UNET Theta Warmup=0
UNET ZTol=0
UNET ZSATol=0
UNET MxIter=0
UNET MaxInSteps=0
UNET DtIC=0
UNET DtMin=0
UNET MaxCRTS=0
UNET WFStab=0
UNET SFStab=0
UNET WFX=0
UNET SFX=0
UNET DSS MLevel=0
UNET DZMax Abort=0
UNET Convert EG Bridges=0
UNET Use Existing IB Tables=0
UNET Froude Limit=0
UNET Froude Power=0
Write IC File=0
Echo Input=False
Echo Output=False
Write Detailed=0

--- CowCr.f01 (steady flow) ---

Flow Title=USGS Regress. Eqn. (2010) - Western-Plateaus
Program Version=4.10
Number of Profiles= 1
Profile Names=P100yr
River Rch & RM=CowCr,Main            ,40061.5
     940
River Rch & RM=CowCr,Main            ,37928.3
    1000
River Rch & RM=CowCr,Main            ,37628.1
    1385
River Rch & RM=CowCr,Main            ,37172.6
    1486
River Rch & RM=CowCr,Main            ,34805
    1561
River Rch & RM=CowCr,Main            ,34387.6
    1735
River Rch & RM=CowCr,Main            ,30208.2
    1864
River Rch & RM=CowCr,Main            ,29286.5
    2102
River Rch & RM=CowCr,Main            ,26140.1
    2226
River Rch & RM=CowCr,Main            ,23708.1
    2342
River Rch & RM=CowCr,Main            ,18909.5
    2483
River Rch & RM=CowCr,Main            ,18263
    2709
Boundary for River Rch & Prof#=CowCr,Main            , 1
Up Type= 0
Dn Type= 3
Dn Slope=0.0025
DSS Import GetInterval= 0
DSS Import GetPeak= 0
DSS Import FillOption= 0

--- CowCr.g01 (geometry) ---

Geom Title=USGS 10m DEM
Program Version=4.10

River Reach=CowCr           ,Main
Reach XY= 30
      1478343.89      302589.475     1476130.218      303226.801
     1475705.218      305044.857     1475042.024      306139.301
     1474825.531      308207.009     1474099.176      308289.287
     1472632.963      310333.878     1472011.922      310448.578
     1470050.279      311965.662     1469910.741      312694.989
     1469078.128      313044.541     1468516.945      312601.773
     1466607.918      312845.132     1465843.534      312348.856
     1465201.347      312405.453     1464860.722      312746.078
      1464933.31      313719.294     1464225.826      313525.245
     1464431.421      314284.031     1462775.826      314896.078
     1462273.048      314549.551     1461086.937      314640.523
     1459679.992      315307.884     1459446.659      314325.245
     1458414.715      314398.162     1457725.941      314728.949
     1457547.894      315642.905     1456550.377      315371.527
     1454851.766      316060.589     1453509.511      317735.359

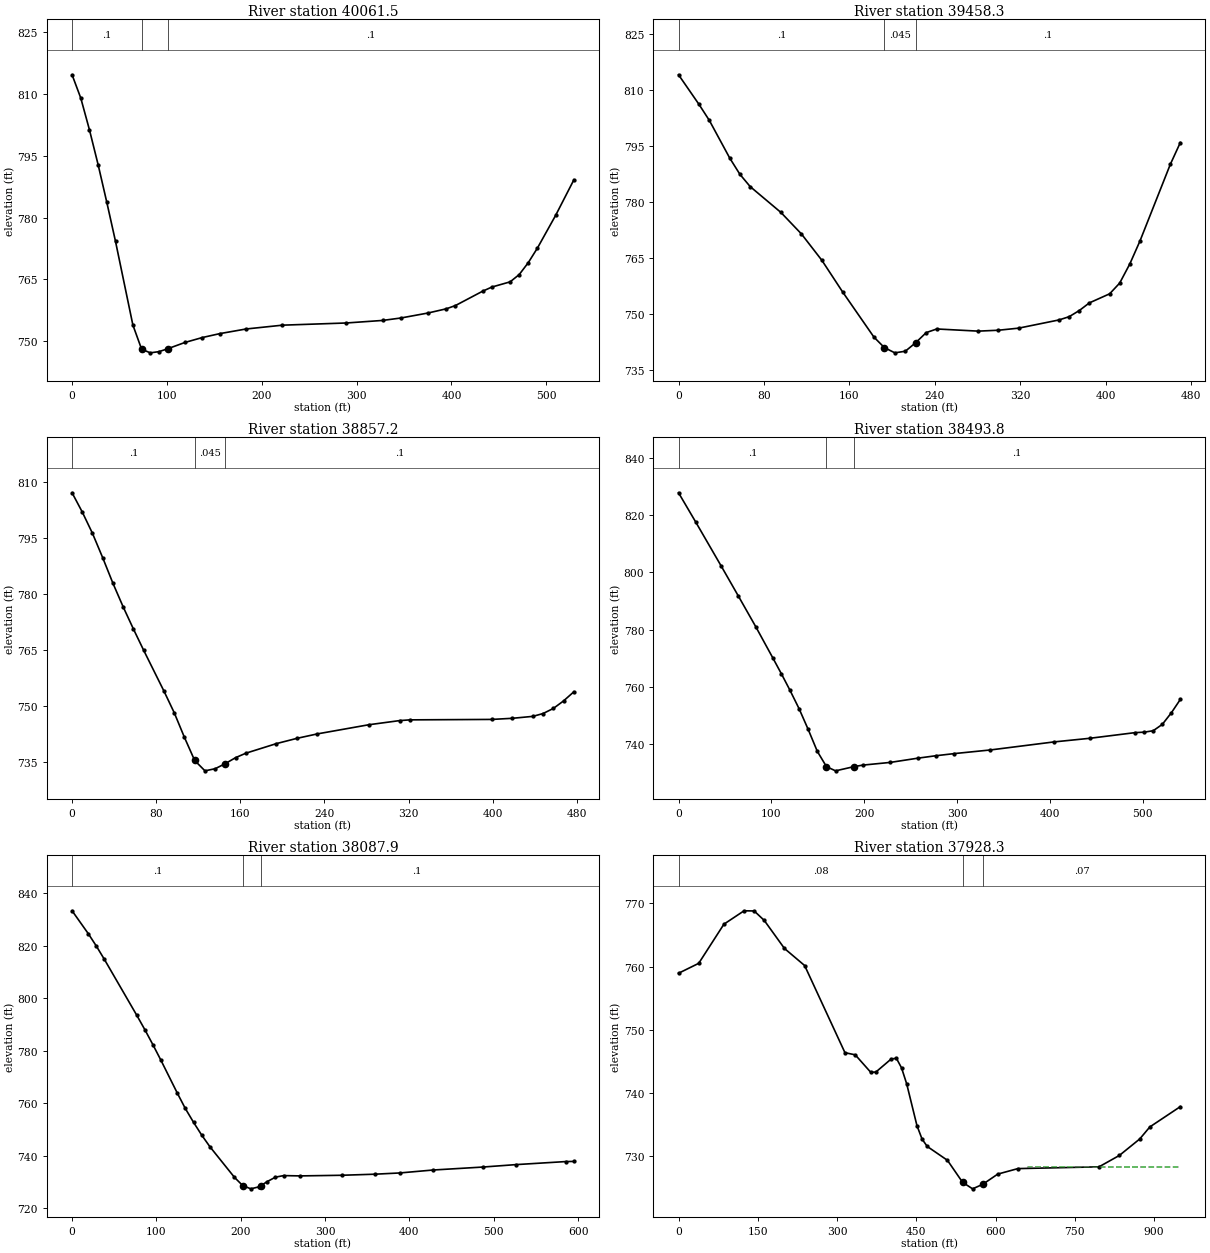
Type RM Length L Ch R = 1 ,40061.5 ,601,603.2,605.5
XS GIS Cut Line= 4
     1478284.709      302524.228     1478339.818      302640.038
     1478360.195      302691.254     1478439.223        303027.7
#Sta/Elev= 30
       0  814.68     9.2  809.01    18.3  801.33    27.5  792.81    36.6  783.73
    45.8  774.21    64.1  753.91    73.3  748.04    82.4  747.15    91.6  747.44
   100.8  748.14   119.1  749.68   137.4  750.87   155.8  751.82   183.4  752.94
   221.8  753.87     289   754.4   327.4  755.02   346.6  755.61   375.4  756.83
   394.6  757.85   404.2  758.64     433  762.14   442.6  763.13   461.8  764.39
   471.4  766.16     481  769.07   490.6   772.6   509.8  780.54     529  789.16
#Mann= 3 , 0 , 0
       0      .1       0    73.3    .045       0   100.8      .1       0
Bank Sta=73.3,100.8
XS Rating Curve= 0 ,0
Exp/Cntr=0.3,0.1

Type RM Length L Ch R = 1 ,39458.3 ,597.3,601.1,604.4
XS GIS Cut Line= 4
      1477748.25      302741.242     1477805.542      302873.186
     1477848.945      302992.978     1477909.709      303182.214
#Sta/Elev= 30
       0  813.98    19.2  806.04    28.8  801.79      48  791.66    57.5  787.33
    67.1  784.05    95.9  777.13   115.1  771.38   134.3   764.3   153.6  755.89
     183  743.77   192.8  740.95   202.6  739.55   212.4  739.98   222.2  742.28
     232  744.97   241.9  745.94   280.7  745.36   299.6   745.6   318.6  746.16
   356.4  748.36   365.9  749.23   375.4  750.88   384.8  752.92   403.8  755.35
   413.2  758.22   422.7  763.35   432.2  769.49   460.6  789.99     470  795.84
#Mann= 3 , 0 , 0
       0      .1       0   192.8    .045       0   222.2      .1       0
Bank Sta=192.8,222.2
XS Rating Curve= 0 ,0
Exp/Cntr=0.3,0.1

Type RM Length L Ch R = 1 ,38857.2 ,358.8,363.4,367.8
XS GIS Cut Line= 3
      1477208.32      302824.575     1477244.778      303015.547
     1477336.792      303282.909
#Sta/Elev= 30
       0  807.19     9.7  802.02    19.4   796.3    29.2   789.7    38.9  782.86
    48.6  776.54    58.3  770.63      68  764.94    87.5  753.86    97.2  748.09
   106.9  741.47   116.6  735.29   126.4  732.51   136.1  733.08   145.8  734.46
   155.5  736.05   165.3  737.25   194.4  739.83   213.9  741.24   233.4  742.44
   282.2  744.89   311.4     746   321.2   746.2   399.2  746.32   418.7  746.62
   438.2  747.14   447.9   747.9   457.7  749.27   467.4  751.29   477.2  753.74
#Mann= 3 , 0 , 0
       0      .1       0   116.6    .045       0   145.8      .1       0
Bank Sta=116.6,145.8
XS Rating Curve= 0 ,0
Exp/Cntr=0.3,0.1

Type RM Length L Ch R = 1 ,38493.8 ,410.5,405.9,400.5
XS GIS Cut Line= 4
     1476868.476      302839.332     1476875.421      302959.124
     1476873.685      303136.207     1476906.671      303377.527
#Sta/Elev= 28
       0  827.71    18.5  817.52    46.2  802.04    64.6  791.63    83.1  781.08
   101.5   770.2   110.8  764.62     120  758.91   129.8   752.5   139.7  745.21
   149.5  737.59   159.4  732.24   169.2  730.79   188.9  732.25   198.7  732.79
   228.2  733.73   257.7   735.2   277.4  736.06   297.1   736.8     336  738.07
   404.2  740.86   443.2  742.14   491.9  744.11   501.7  744.27   511.4  744.77
   521.2  746.99   530.9     751   540.6  755.68
#Mann= 3 , 0 , 0
       0      .1       0   159.4    .045       0   188.9      .1       0
Bank Sta=159.4,188.9
XS Rating Curve= 0 ,0
Exp/Cntr=0.3,0.1

Type RM Length L Ch R = 1 ,38087.9 ,165.7,159.6,153.9
XS GIS Cut Line= 4
     1476490.004      302841.068     1476502.157      302974.749
     1476529.935      303098.013     1476696.601      303387.943
#Sta/Elev= 30
       0   833.3    19.2  824.59    28.8  819.84    38.4  814.73    76.7  793.48
    86.3  787.98    95.9  782.22   105.5  776.24   124.6  763.92   134.2  757.98
     144  752.68   153.7   747.8   163.4  743.38   192.6  731.67   202.3  728.57
     212  727.31   221.7  728.09   223.6  728.48   231.4  730.07   241.2  731.77
   250.9  732.36   270.4  732.24   319.6  732.48     359  732.89   388.4  733.36
   427.8  734.48   486.8  735.61   526.2  736.54   585.2   737.7     595  737.76
#Mann= 3 , 0 , 0
       0      .1       0   202.3    .045       0   223.6      .1       0
Bank Sta=202.3,223.6
XS Rating Curve= 0 ,0
Exp/Cntr=0.3,0.1

Type RM Length L Ch R = 1 ,37928.3 ,137,135.3,133.2
XS GIS Cut Line= 5
      1476179.24      302589.332     1476262.573      302893.152
     1476340.698      303038.985     1476426.202      303209.124
     1476592.435      303433.082
#Sta/Elev= 30
       0  758.95    38.2  760.52    85.9  766.71   124.1  768.83   143.2   768.8
   162.3   767.3   200.5  762.87   238.7  760.17     315  746.39   334.5  746.05
   363.7   743.3   373.4  743.32   402.6   745.4   412.4   745.5   422.1  743.99
   431.8  741.48   451.3  734.85     461  732.72   470.8  731.56     509  729.37
   537.6   725.9   556.6  724.86   575.7  725.57   604.2  727.19   642.3  728.06
   795.9  728.34   834.4  730.14   872.9  732.74   892.1  734.65   949.8  737.86
#Mann= 3 , 0 , 0
       0     .08       0   537.6    .045       0   575.7     .07       0
#XS Ineff= 2 , 0
                          661.69          728.28
Permanent Ineff=
       F       F
Bank Sta=537.6,575.7
XS Rating Curve= 0 ,0
Exp/Cntr=0.3,0.1

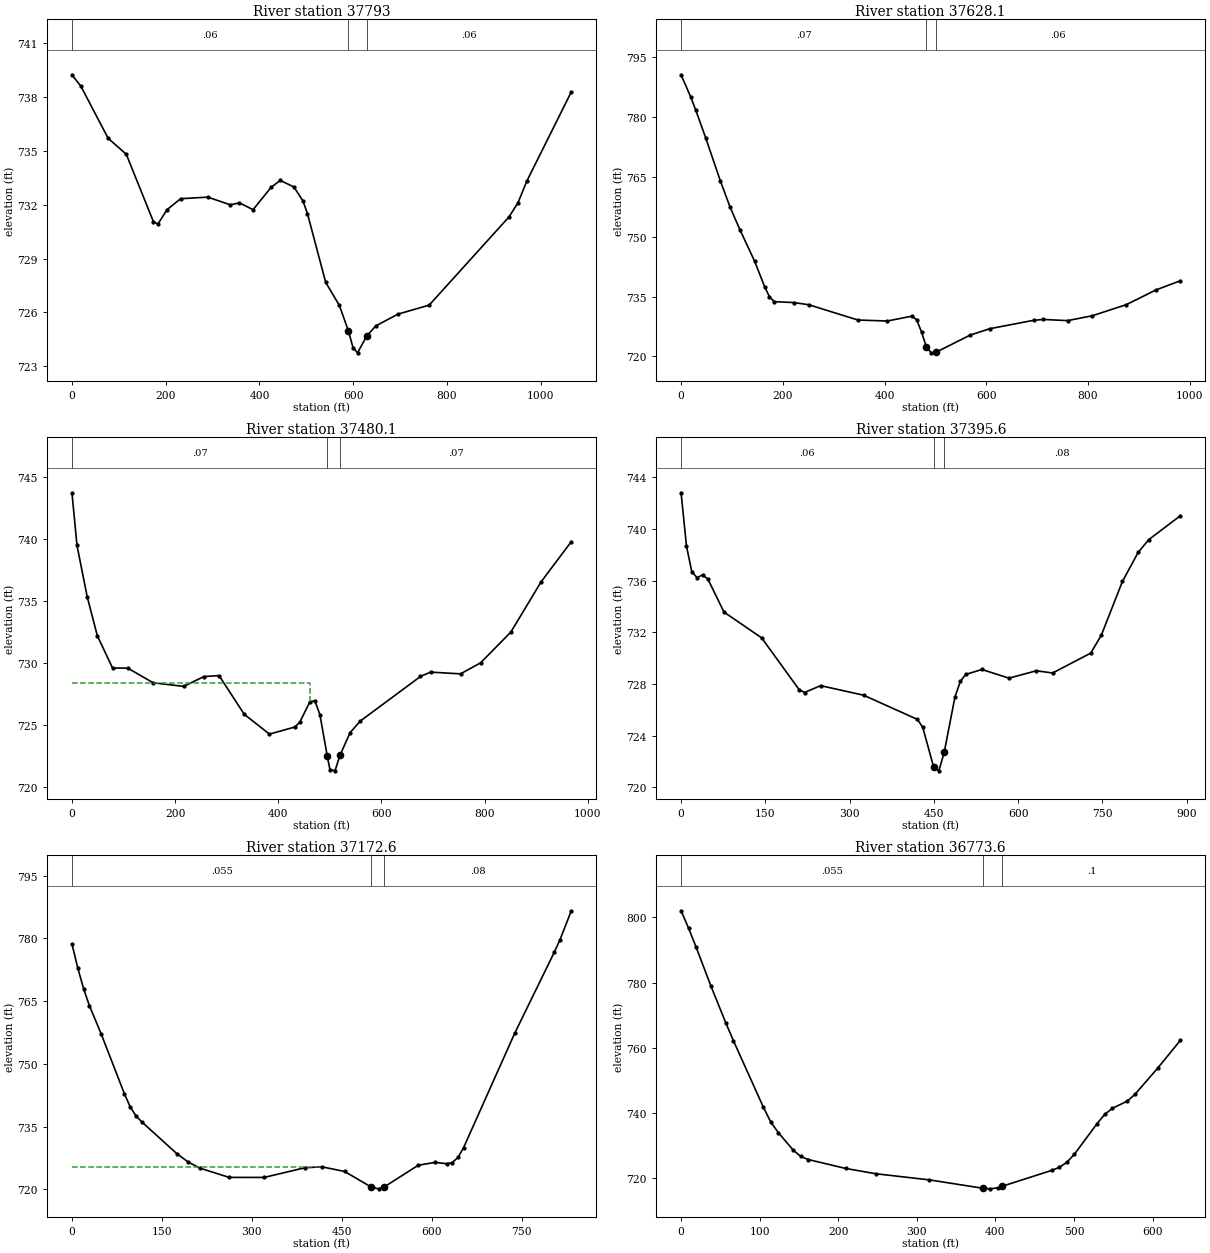
Type RM Length L Ch R = 1 ,37793   ,172.4,164.9,157.3
XS GIS Cut Line= 6
     1476033.407      302565.027     1476105.889      302865.374
      1476170.56      303016.416     1476271.254      303170.929
     1476396.254      303349.749     1476557.712      303448.707
#Sta/Elev= 30
       0  739.25    19.3   738.6    77.2  735.71   115.9  734.82   173.8  731.06
   183.4  730.93   202.8  731.73   231.7  732.34   289.7  732.43     338     732
   357.3  732.11   386.3  731.73     425  732.98   444.3  733.36   473.3     733
   492.7  732.22   502.4  731.51   541.2  727.68   570.3   726.4   589.8  724.97
   599.5  724.04   609.2  723.75   628.6  724.68     648  725.25   695.6  725.91
     762  726.41   932.7  731.34   951.6  732.13   970.6  733.34  1065.2   738.3
#Mann= 3 , 0 , 0
       0     .06       0   589.8    .045       0   628.6     .06       0
Bank Sta=589.8,628.6
XS Rating Curve= 0 ,0
Exp/Cntr=0.3,0.1

Type RM Length L Ch R = 1 ,37628.1 ,162.9,148,132.6
XS GIS Cut Line= 5
     1475717.435      302958.256     1476083.754      303209.124
     1476280.803      303361.034     1476374.553      303380.131
     1476550.768      303459.124
#Sta/Elev= 30
       0  790.62    19.3  784.95      29  781.71    48.3  774.84    77.2  764.01
    96.5  757.39   115.8  751.74   144.8  743.81   164.1  737.52   173.7  734.96
   183.4  733.73     222   733.5     251  732.96   347.5  729.13   405.4  728.88
   453.6  730.09   463.1   729.2   472.7   726.1   482.3  722.35   491.8   720.9
   501.4  721.07   568.4  725.36   606.7  726.95   692.8  729.05   711.9  729.27
   759.8  728.98   807.8  730.18   875.4  732.99   933.3  736.66   981.6  738.98
#Mann= 3 , 0 , 0
       0     .07       0   482.3    .045       0   501.4     .06       0
Bank Sta=482.3,501.4
XS Rating Curve= 0 ,0
Exp/Cntr=0.3,0.1

Type RM Length L Ch R = 1 ,37480.1 ,84.9,84.5,84.1
XS GIS Cut Line= 5
     1475594.171      303410.513     1475868.476      303386.207
      1476210.49      303382.735     1476375.421      303387.943
     1476541.219      303471.277
#Sta/Elev= 30
       0  743.72     9.8  739.47    29.5  735.35    49.2  732.19    78.7  729.59
   108.2  729.58   157.4   728.4   216.4  728.11   255.7   728.9   285.2  728.98
     334  725.86   382.9  724.26   431.7  724.83   441.5  725.21     461  726.85
   470.8  726.96   480.6  725.84     495  722.47   500.1   721.4   509.9   721.3
   519.7  722.57   539.2  724.38   558.8  725.31   675.6  728.91   695.1  729.26
   753.3  729.12   792.2  730.01   850.8  732.49   909.4  736.54     968  739.78
#Mann= 3 , 0 , 0
       0     .07       0     495    .045       0   519.7     .07       0
#XS Ineff= 2 , 0
          460.73   728.4
Permanent Ineff=
       F       F
Bank Sta=495,519.7
XS Rating Curve= 0 ,0
Exp/Cntr=0.3,0.1

Type RM Length L Ch R = 1 ,37395.6 ,220.8,222.9,224.5
XS GIS Cut Line= 5
     1475632.148      303477.136     1475928.372      303472.796
     1476186.619        303465.2      1476360.23      303444.584
     1476512.139      303493.412
#Sta/Elev= 30
       0  742.79     9.6  738.68    19.1  736.68    28.7  736.22    38.2  736.44
    47.8  736.11    76.4  733.56   143.4  731.57   210.2  727.56   219.8  727.34
   248.5  727.87     325  727.13   420.6  725.26   430.2  724.65   449.4  721.61
   458.9  721.28   468.5  722.72   487.6     727   497.2   728.2   506.8  728.74
   535.5  729.12   583.8  728.45   632.3  729.02   661.5  728.85   729.4  730.39
   748.2  731.78   785.8  735.94   813.9  738.19   832.7  739.17     889  741.02
#Mann= 3 , 0 , 0
       0     .06       0   449.4    .045       0   468.5     .08       0
Bank Sta=449.4,468.5
XS Rating Curve= 0 ,0
Exp/Cntr=0.3,0.1

Type RM Length L Ch R = 1 ,37172.6 ,389.4,399.1,408.6
XS GIS Cut Line= 4
      1475582.38      303604.596     1475973.005      303680.984
     1476190.018      303691.401     1476396.616      303759.109
#Sta/Elev= 30
       0  778.73     9.7  772.94    19.4     768    29.1  763.93    48.5  757.26
    87.4  742.88    97.1  739.73   106.8  737.55   116.5  736.12   174.7  728.55
   194.2  726.49   213.6  725.05   262.1  722.85   320.4  722.84   388.3  725.15
   416.9  725.38   454.7  724.26   499.2  720.52   511.4  720.11   520.8  720.57
   577.5  725.76   605.8  726.44   624.7  726.12   634.2   726.4   643.6  727.61
   653.1  729.98   738.2   757.3   804.3  776.71   813.8  779.71   832.7  786.63
#Mann= 3 , 0 , 0
       0    .055       0   499.2    .045       0   520.8     .08       0
#XS Ineff= 2 , 0
          418.23  725.35
Permanent Ineff=
       F       F
Bank Sta=499.2,520.8
XS Rating Curve= 0 ,0
Exp/Cntr=0.3,0.1

Type RM Length L Ch R = 1 ,36773.6 ,256.6,248.5,240.4
XS GIS Cut Line= 4
     1475535.505      303823.346     1475743.838      303917.096
     1475976.477      304038.623     1476108.421      304097.651
#Sta/Elev= 30
       0  801.99     9.5  796.67      19  790.94    38.1  778.86    57.1  767.53
    66.6  762.19   104.7  741.83   114.2  737.24   123.8     734   142.8  728.62
   152.3  726.73   161.8  725.77   209.4  723.04   247.9  721.41   315.9  719.54
     384  716.97   393.7  716.79   403.4  717.13   408.8  717.59   471.5  722.43
   481.2  723.36   490.9  724.92   500.6  727.41   529.5  736.81   539.1  739.61
   548.7  741.43     568  743.69   577.6  745.74   606.6  753.79   635.5  762.32
#Mann= 3 , 0 , 0
       0    .055       0     384    .045       0   408.8      .1       0
Bank Sta=384,408.8
XS Rating Curve= 0 ,0
Exp/Cntr=0.3,0.1

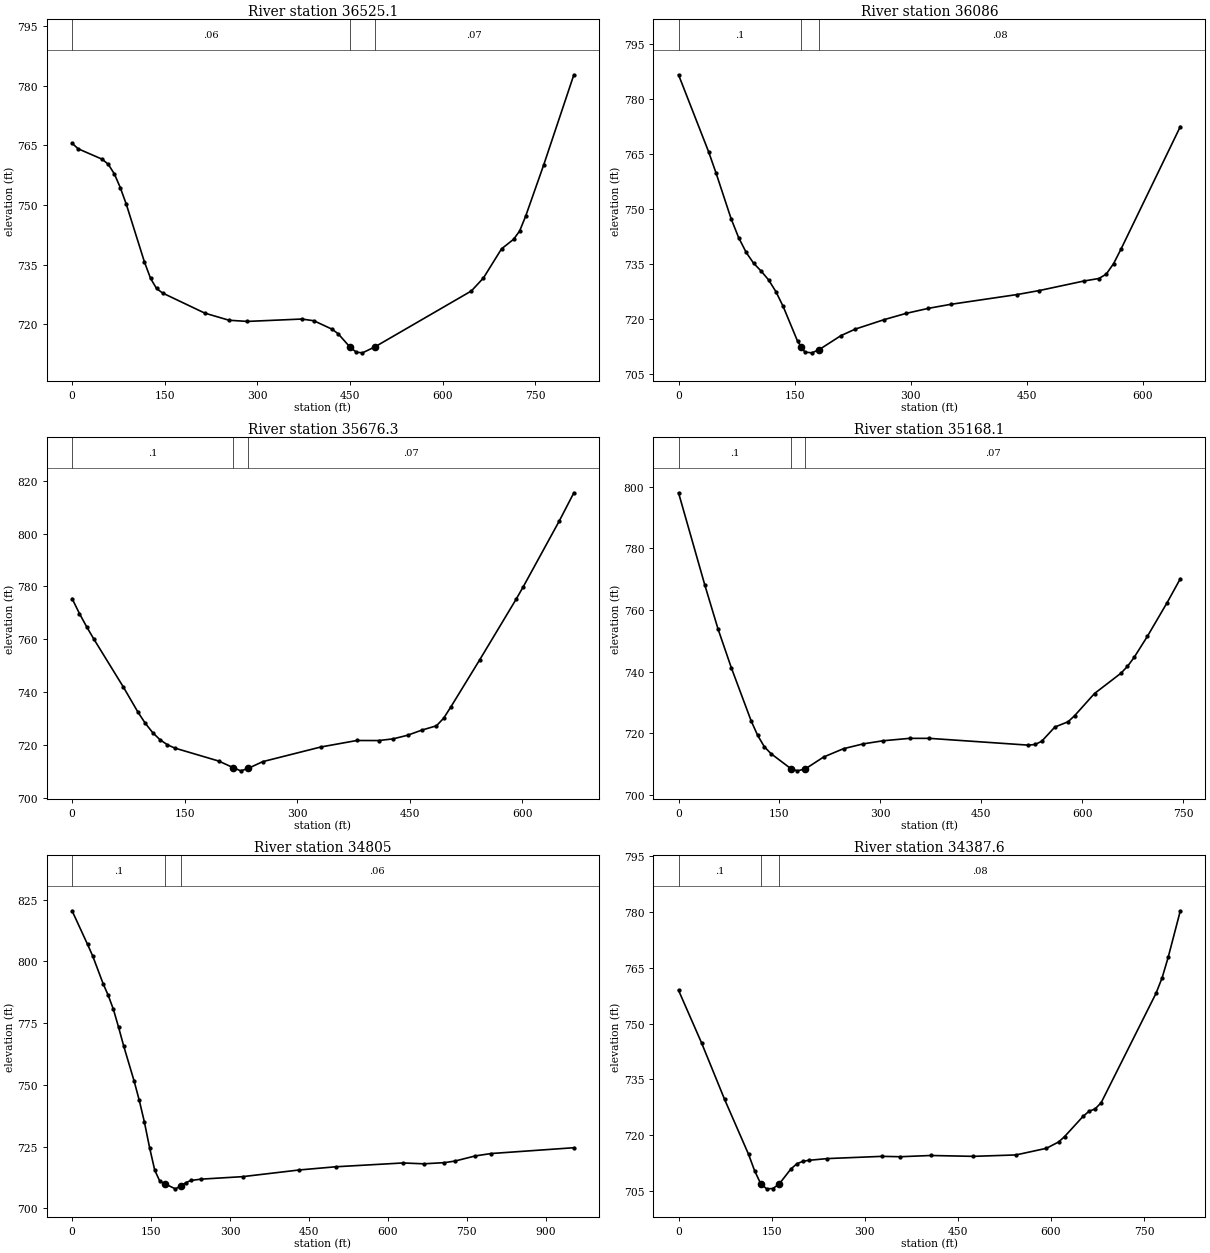
Type RM Length L Ch R = 1 ,36525.1 ,437.9,439.1,439.5
XS GIS Cut Line= 4
     1475321.963       304267.79     1475538.977      304179.248
     1475889.671      304222.651     1476106.685      304279.943
#Sta/Elev= 30
       0  765.54     9.8  764.14    48.8  761.51    58.6  760.23    68.4  757.83
    78.1  754.36    87.9  750.13   117.2  735.64     127  731.56   136.7  729.01
   146.5  727.86   214.8  722.81     254  721.02   283.5  720.72   371.8  721.32
   391.4  720.89   420.9  718.76   430.7  717.62   450.3  714.18   460.2  712.98
     470  712.82   489.6  714.27   646.3  728.38   665.8  731.64   695.1  738.97
   714.6  741.37   724.4  743.45   734.1  747.16   763.4  760.09   812.2  782.75
#Mann= 3 , 0 , 0
       0     .06       0   450.3    .045       0   489.6     .07       0
Bank Sta=450.3,489.6
XS Rating Curve= 0 ,0
Exp/Cntr=0.3,0.1

Type RM Length L Ch R = 1 ,36086   ,411,409.8,407.6
XS GIS Cut Line= 4
     1475441.755      304616.748     1475556.338      304595.915
     1475731.685      304623.693     1476078.907      304694.873
#Sta/Elev= 30
       0  786.51    38.8  765.58    48.5  759.74    67.9  747.34    77.6   742.2
    87.4  738.15      97   735.2   106.8  733.05   116.5  730.62   125.8  727.47
   135.2  723.43   153.8  713.97  158.55712.4692   163.2     711   172.5   710.8
   181.9   711.7   209.9  715.49   228.6  717.28     266  719.86     294  721.54
   322.7  722.91   351.5     724   437.7  726.68   466.4  727.77   523.9  730.36
   543.1  731.04   552.6  732.21   562.2   735.1   571.8  739.07   648.4  772.41
#Mann= 3 , 0 , 0
       0      .1       0  158.55    .045       0   181.9     .08       0
Bank Sta=158.55,181.9
XS Rating Curve= 0 ,0
Exp/Cntr=0.3,0.1

Type RM Length L Ch R = 1 ,35676.3 ,498.4,508.1,514.8
XS GIS Cut Line= 3
     1475474.741      304979.596     1475737.991      304996.329
     1476141.014      305033.731
#Sta/Elev= 30
       0  775.43     9.8  769.77    19.5  764.71    29.3  759.96    68.4  741.92
    87.9  732.39    97.7  728.17   107.5  724.67   117.2     722     127  720.11
   136.8  718.86   195.4  713.94   214.9  711.41   224.7  710.24   234.5  711.15
     254  713.72   331.2  719.25   379.4  721.72   408.3   721.7   427.6  722.33
   446.9   723.7   466.2  725.67   485.4  727.28   495.1  730.17   504.7  734.46
   543.3  752.36   591.4  775.09   601.1   779.9   649.3  804.91   668.5  815.45
#Mann= 3 , 0 , 0
       0      .1       0   214.9    .045       0   234.5     .07       0
Bank Sta=214.9,234.5
XS Rating Curve= 0 ,0
Exp/Cntr=0.3,0.1

Type RM Length L Ch R = 1 ,35168.1 ,364.6,363.1,361.7
XS GIS Cut Line= 4
     1475316.755      305333.762     1475401.698      305382.615
      1475610.45      305491.481     1475988.133      305656.365
#Sta/Elev= 30
       0     798    39.2  767.98    58.8  753.76    78.4   741.3   107.8  724.11
   117.6  719.33   127.4   715.7   137.2  713.46   166.7   708.6   176.5  707.86
   188.3  708.48   215.7  712.36   245.1  715.04   274.6  716.61     304  717.61
   343.2  718.39   372.7  718.39   519.8  716.19   529.7   716.4   539.5  717.44
   559.1  722.06   578.7  723.77   588.5  725.75     618  732.93   657.2  739.49
     667  741.74   676.8  744.61   696.5  751.44   725.9  762.39   745.5  770.15
#Mann= 3 , 0 , 0
       0      .1       0   166.7    .045       0   188.3     .07       0
Bank Sta=166.7,188.3
XS Rating Curve= 0 ,0
Exp/Cntr=0.3,0.1

Type RM Length L Ch R = 1 ,34805   ,421.1,417.4,414.4
XS GIS Cut Line= 3
     1475086.688      305611.874       1475428.3      305761.264
     1475971.792      305964.565
#Sta/Elev= 30
       0  820.52    29.4  806.92    39.2  802.21    58.9  791.04    68.7  786.26
    78.5  780.61    88.3   773.4    98.1  765.73   117.7   751.7   127.6  743.81
   137.4  734.95   147.2  724.66     157   715.5   166.8  710.97   176.6  709.93
   196.2  707.94     206  709.04   215.9  710.42   225.7  711.33   245.3  711.87
   323.8  712.87   431.9  715.59   500.7  716.87   628.6  718.42   667.9  718.07
   707.2  718.55   726.9  719.17   766.2  721.28   795.8  722.23   953.1  724.59
#Mann= 3 , 0 , 0
       0      .1       0   176.6    .045       0     206     .06       0
Bank Sta=176.6,206
XS Rating Curve= 0 ,0
Exp/Cntr=0.3,0.1

Type RM Length L Ch R = 1 ,34387.6 ,461.5,463.7,465.3
XS GIS Cut Line= 4
     1474954.744      306041.735     1475038.132      306045.315
     1475218.317      306089.491     1475704.865      306322.638
#Sta/Elev= 30
       0  758.93    37.1   744.8    74.2  729.62   112.8  714.86   122.5  710.47
   132.3  706.99     142  705.58   151.8  705.67   161.6  706.76   181.1  710.93
   190.9  712.34   200.6  712.99   210.4  713.25   239.7  713.71   327.8  714.31
   357.3  714.21   406.3  714.54     475  714.31   543.6  714.69   592.7  716.47
   612.3  718.17   622.1  719.64   651.6  725.02   661.4  726.43   671.2  727.06
     681  728.74   769.3  758.11   779.1  762.26   788.9  767.78   808.5   780.3
#Mann= 3 , 0 , 0
       0      .1       0   132.3    .045       0   161.6     .08       0
Bank Sta=132.3,161.6
XS Rating Curve= 0 ,0
Exp/Cntr=0.3,0.1

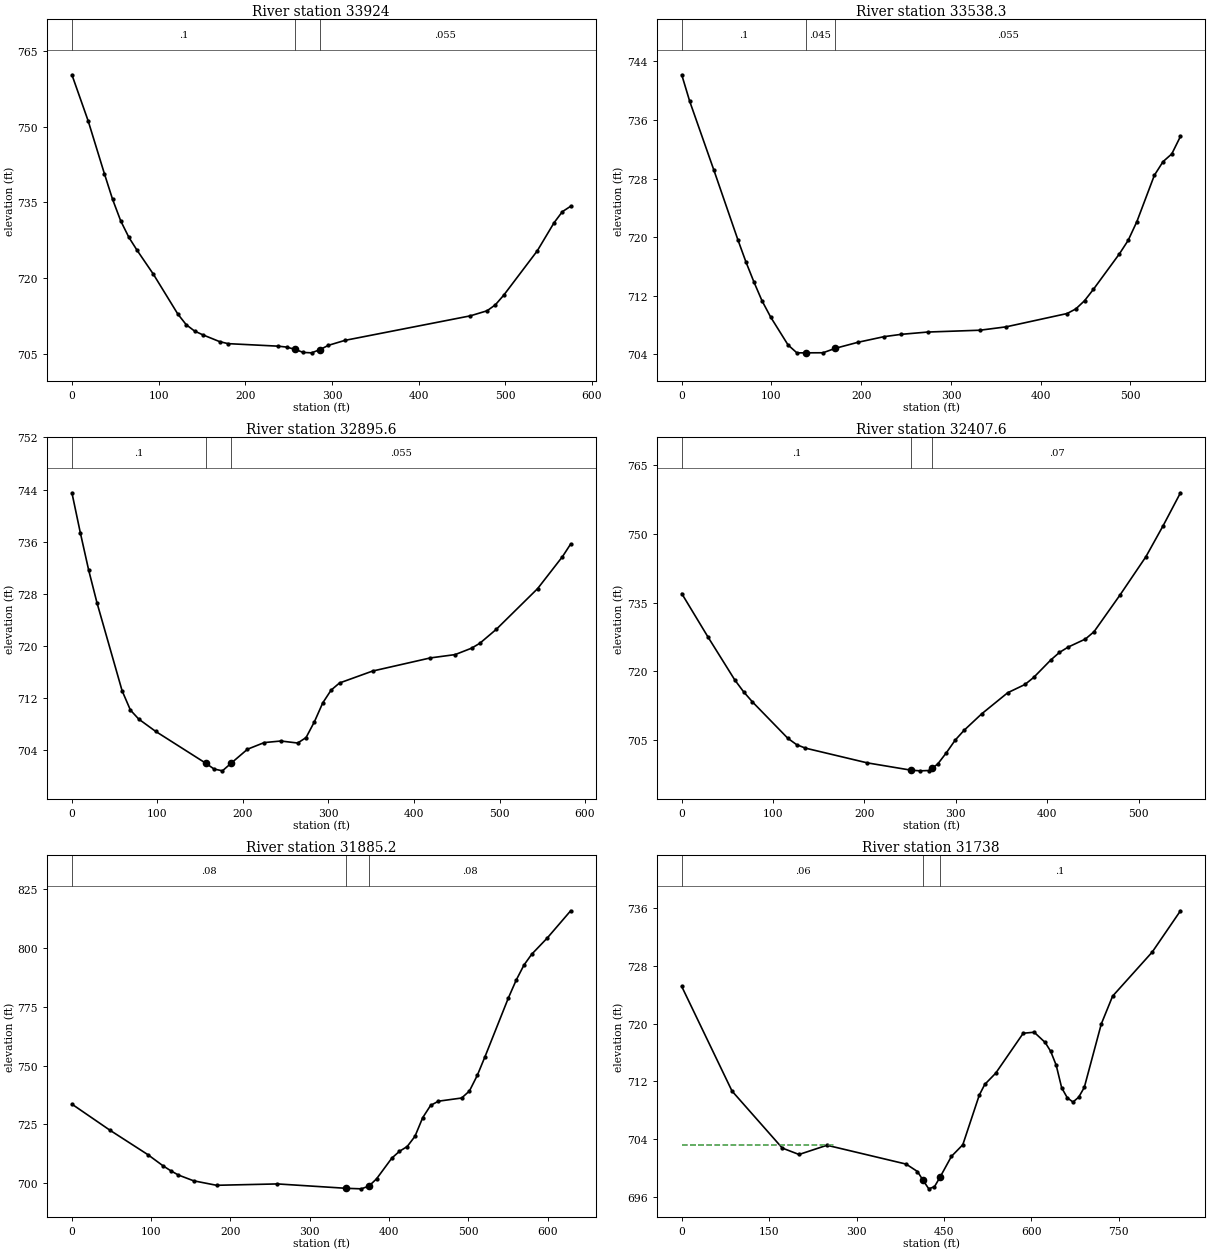
Type RM Length L Ch R = 1 ,33924   ,388.4,385.6,382.4
XS GIS Cut Line= 3
      1474831.48      306411.527     1474937.382      306449.721
     1475378.355      306590.346
#Sta/Elev= 30
       0  760.24    18.8  751.09    37.5  740.66    46.9  735.61    56.3  731.34
    65.7  728.09      75  725.57    93.8  720.84   122.2  712.91   131.9   710.8
   141.5  709.55   151.2  708.79   170.4  707.46   180.1  707.06   237.9  706.56
   247.6  706.38   257.2  705.94   266.9  705.32   276.5  705.24   286.2  705.88
   295.8  706.72   315.1  707.71   459.7  712.56     479  713.56   488.6  714.75
   498.3  716.67   536.9  725.42   556.2  730.96   565.8  733.16   575.4  734.23
#Mann= 3 , 0 , 0
       0      .1       0   257.2    .045       0   286.2    .055       0
Bank Sta=257.2,286.2
XS Rating Curve= 0 ,0
Exp/Cntr=0.3,0.1

Type RM Length L Ch R = 1 ,33538.3 ,644.2,642.8,640.2
XS GIS Cut Line= 3
     1474746.237      306835.832     1474833.476      306816.301
      1475291.81      306902.239
#Sta/Elev= 30
       0  742.18     8.9  738.55    35.8  729.16    62.6  719.63    71.5  716.63
    80.5  713.86    89.4  711.32    99.1  709.08   118.5  705.27   128.3   704.2
     138   704.2   157.4  704.21   171.2  704.82   196.3  705.64   225.4  706.41
   244.8  706.73     274  707.04   332.3  707.29   361.4  707.75   429.4  709.57
   439.1   710.2   448.8  711.32   458.6  712.86   487.7  717.73   497.4  719.56
   507.1  722.12   526.6  728.45   536.3  730.32     546  731.37   555.7  733.77
#Mann= 3 , 0 , 0
       0      .1       0     138    .045       0   171.2    .055       0
Bank Sta=138,171.2
XS Rating Curve= 0 ,0
Exp/Cntr=0.3,0.1

Type RM Length L Ch R = 1 ,32895.6 ,480.9,488,494.3
XS GIS Cut Line= 3
     1474826.592      307371.918      1475137.79       307404.47
      1475387.79      307507.334
#Sta/Elev= 30
       0  743.51     9.8  737.39    19.6  731.63    29.3  726.62    58.7   713.1
    68.4  710.14    78.2  708.75    97.8  706.88   156.4  701.99   166.2  701.09
     176  700.81   185.8  701.94   205.3  704.13   224.9  705.15   244.4  705.39
     264  705.08   273.8  705.92   283.6  708.36   293.3  711.24   303.1  713.21
   312.9   714.3   351.5  716.13   419.1  718.15   448.1  718.66   467.4  719.65
     477   720.4   496.3  722.55   544.6   728.8   573.6   733.7   583.2  735.64
#Mann= 3 , 0 , 0
       0      .1       0   156.4    .045       0   185.8    .055       0
Bank Sta=156.4,185.8
XS Rating Curve= 0 ,0
Exp/Cntr=0.3,0.1

Type RM Length L Ch R = 1 ,32407.6 ,510.2,522.4,533
XS GIS Cut Line= 4
     1474745.863      307707.855     1474899.509      307766.449
     1475059.665      307832.855     1475252.374       307910.98
#Sta/Elev= 30
       0  736.96      29   727.4      58  718.14    67.7  715.54    77.4  713.33
   116.1   705.4   125.8     704   135.4  703.25     203  700.04   251.1  698.44
   260.8   698.3   270.4  698.37  274.33698.9349     280  699.75   289.7  702.27
   299.3  705.01   308.9  707.12   328.2  710.72   356.7  715.33   375.6  717.13
   385.1  718.66     404   722.5   413.4  724.13   422.9  725.29   441.8  727.05
   451.2  728.64   479.6  736.64     508  745.01   526.9  751.79   545.8  758.94
#Mann= 3 , 0 , 0
       0      .1       0   251.1    .045       0  274.33     .07       0
Bank Sta=251.1,274.33
XS Rating Curve= 0 ,0
Exp/Cntr=0.3,0.1

Type RM Length L Ch R = 1 ,31885.2 ,143.3,147.2,151.6
XS GIS Cut Line= 4
     1474609.145      307888.845     1474674.249      307959.157
     1474885.186      308196.136     1475067.478      308312.022
#Sta/Elev= 30
       0  733.56    47.9  722.48    95.8  712.07     115   707.3   124.7  705.21
   134.3   703.4   153.5  700.94   182.4  699.03   259.3  699.61   345.8  697.75
     365  697.52   374.6  698.69   384.2  701.75   403.5  710.58   413.1  713.48
   422.9  715.52   432.7  719.86   442.5  727.83   452.4     733   462.2  734.81
   491.6  736.17   501.4  739.15   511.3  745.78   521.1   753.8   550.5  778.72
   560.4  786.34   570.2  792.74     580  797.36   599.6  804.26   629.1  815.84
#Mann= 3 , 0 , 0
       0     .08       0   345.8    .045       0   374.6     .08       0
Bank Sta=345.8,374.6
XS Rating Curve= 0 ,0
Exp/Cntr=0.3,0.1

Type RM Length L Ch R = 1 ,31738   ,70.3,70.8,72.5
XS GIS Cut Line= 5
     1474521.905      307937.022     1474691.176      308145.355
     1474803.155      308327.647     1474900.225      308466.865
      1475062.27      308590.668
#Sta/Elev= 30
       0  725.16    86.3  710.67   172.6  702.77   201.3  701.88   249.3  703.16
   385.1  700.55   404.6  699.52   414.3  698.29     424  697.12   433.8  697.42
   443.5  698.76   462.9  701.62   482.4  703.23   510.7  710.11   520.1  711.59
   538.9  713.15   586.1  718.68   604.9  718.82   623.8   717.4   633.2  716.18
   642.7  714.25   652.1  711.12   661.8  709.73   671.5  709.15   681.2  709.81
   690.9  711.17   720.1  719.97   739.5  723.82   807.5  729.93     856  735.65
#Mann= 3 , 0 , 0
       0     .06       0   414.3    .045       0   443.5      .1       0
#XS Ineff= 2 , 0
          260.33  703.13
Permanent Ineff=
       F       F
Bank Sta=414.3,443.5
XS Rating Curve= 0 ,0
Exp/Cntr=0.3,0.1

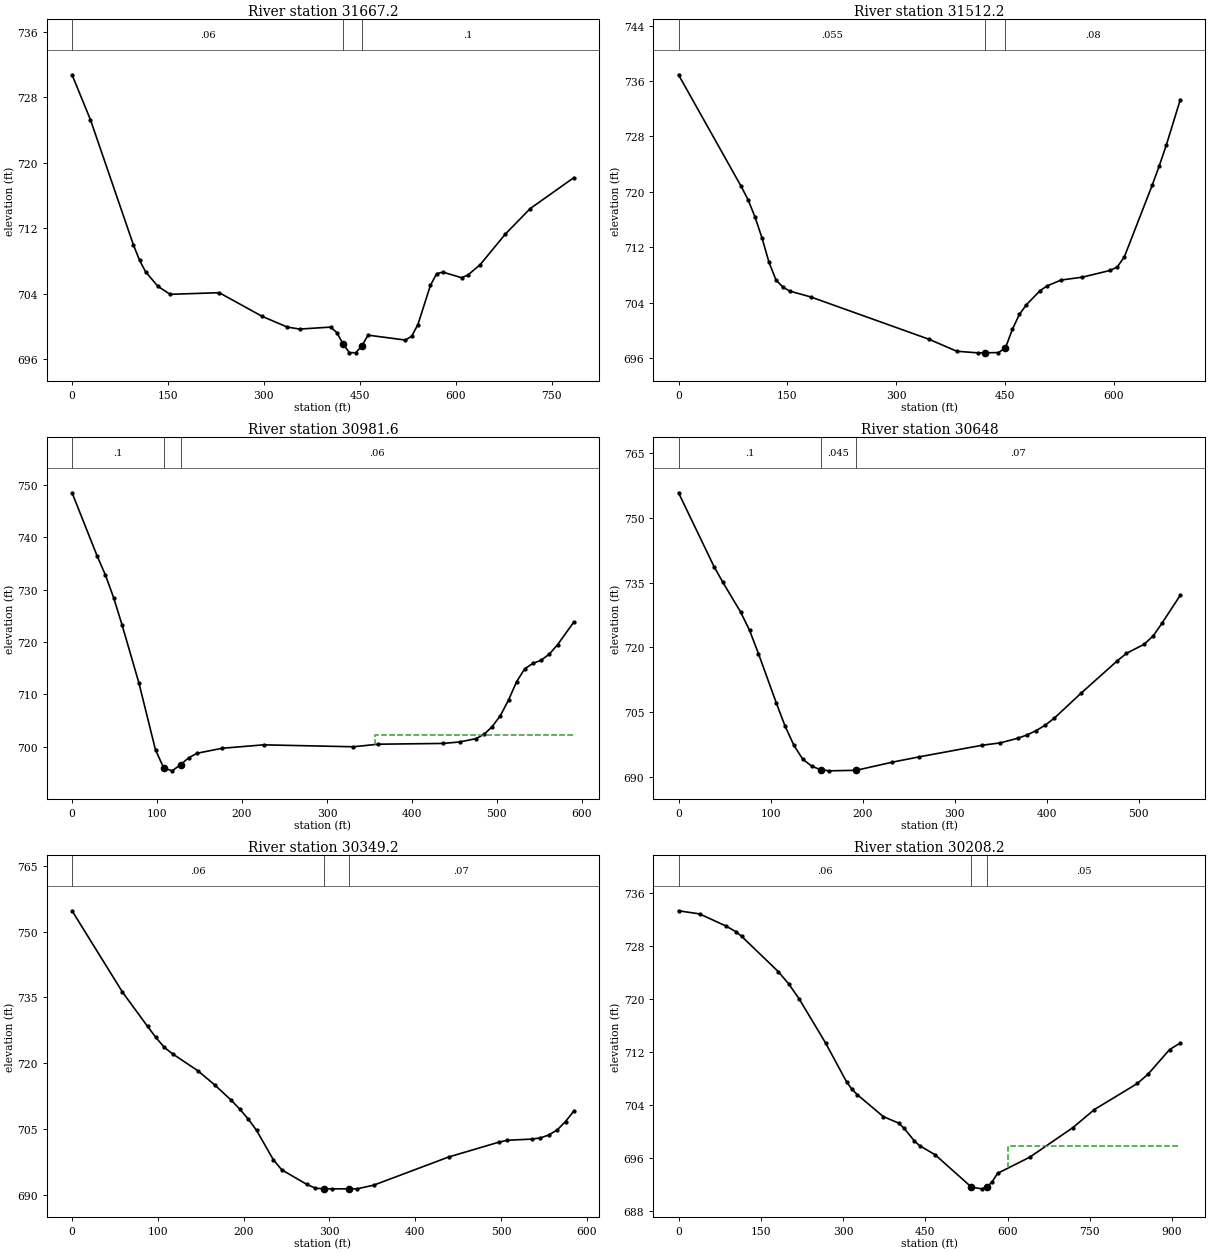
Type RM Length L Ch R = 1 ,31667.2 ,151.8,154.9,156.7
XS GIS Cut Line= 4
      1474475.03      307965.668     1474644.301      308174.001
     1474728.936      308338.063     1474847.426      308647.959
#Sta/Elev= 30
       0  730.73    28.8  725.23    95.9  709.98   105.5   708.1     115  706.69
   134.2  704.92   153.4  703.94   230.1  704.14   297.6  701.24   336.4  699.95
   355.9   699.7   404.5  699.94   414.2  699.26   423.9  697.88   433.6  696.84
   443.3   696.8     453   697.6   462.8  698.96   521.3  698.36   531.1  698.82
   540.9  700.25   560.4  705.02   570.1  706.45   579.9  706.65   609.2  705.97
   618.9  706.28   638.4  707.57   677.5  711.28   716.5   714.4   784.8  718.18
#Mann= 3 , 0 , 0
       0     .06       0   423.9    .045       0     453      .1       0
Bank Sta=423.9,453
XS Rating Curve= 0 ,0
Exp/Cntr=0.3,0.1

Type RM Length L Ch R = 1 ,31512.2 ,537.9,530.7,522.2
XS GIS Cut Line= 4
     1474404.211      307975.071     1474492.753       308145.21
     1474596.919      308433.405     1474635.114      308622.641
#Sta/Elev= 30
       0   736.9    86.3   720.8    95.9  718.86   105.5  716.35   115.1  713.33
   124.7  709.83   134.3   707.3   143.8  706.28   153.4   705.7   182.2  704.86
     345  698.76   383.3  697.03     412   696.8   421.6   696.8   440.8  696.84
   450.4  697.52   459.9  700.18   469.5  702.33   479.1  703.72   498.2  705.78
   507.9  706.46   527.2   707.3   556.2  707.71   594.8  708.69   604.4  709.18
   614.1  710.62   652.7  721.02   662.3  723.78     672  726.76   691.3  733.33
#Mann= 3 , 0 , 0
       0    .055       0   421.6    .045       0   450.4     .08       0
Bank Sta=421.6,450.4
XS Rating Curve= 0 ,0
Exp/Cntr=0.3,0.1

Type RM Length L Ch R = 1 ,30981.6 ,336.5,333.6,331.6
XS GIS Cut Line= 3
     1474055.253      308179.933     1474176.781      308346.599
     1474317.406      308704.238
#Sta/Elev= 30
       0  748.52    29.5  736.44    39.3  732.78    49.1  728.38    58.9  723.22
    78.6   712.2    98.2  699.36   107.9   695.9   117.9  695.36   127.7  696.55
   137.5  697.88   147.3  698.73   176.8  699.68   225.5  700.33   331.2  699.96
     360  700.45   436.8   700.6   456.1  700.88   475.3  701.51   484.9  702.33
   494.5  703.82   504.1  705.92   513.7   708.9   523.3  712.43   532.9  714.89
   542.5   715.9   552.1  716.51   561.7  717.68   571.4  719.47   590.6  723.81
#Mann= 3 , 0 , 0
       0      .1       0   107.9    .045       0   127.7     .06       0
#XS Ineff= 2 , 0
                          356.02          702.13
Permanent Ineff=
       F       F
Bank Sta=107.9,127.7
XS Rating Curve= 0 ,0
Exp/Cntr=0.3,0.1

Type RM Length L Ch R = 1 ,30648   ,296.6,298.8,297.6
XS GIS Cut Line= 3
     1473765.322      308379.585     1473884.799      308505.519
     1474140.322      308775.419
#Sta/Elev= 30
       0  755.81    38.6   738.7    48.2  735.06    67.5  728.17    77.2  723.94
    86.8  718.58   106.1  707.21   115.7   701.8   125.4  697.29     135  694.09
   144.7   692.5   154.3  691.65     164   691.4   193.2  691.53   232.3  693.41
   261.6  694.64   330.1  697.34   349.6  697.87   369.2  698.98     379  699.74
   388.8  700.73   398.6  702.01   408.3  703.59   437.7  709.44   476.8  716.88
   486.6   718.6   506.1  720.73   515.9  722.68   525.7  725.71   545.3  732.09
#Mann= 3 , 0 , 0
       0      .1       0   154.3    .045       0   193.2     .07       0
Bank Sta=154.3,193.2
XS Rating Curve= 0 ,0
Exp/Cntr=0.3,0.1

Type RM Length L Ch R = 1 ,30349.2 ,146,141,137.9
XS GIS Cut Line= 3
     1473567.406      308509.794     1473752.421       308749.69
     1473940.669      308959.446
#Sta/Elev= 30
       0  754.72    58.6  736.24      88  728.38    97.7  725.88   107.5  723.62
   117.3  722.12   146.6  718.29   166.1  715.09   185.7  711.54   195.4  709.56
   205.2  707.33     215  704.72   234.5  698.05   244.3  695.74   273.6  692.41
   283.4  691.55   293.2  691.41     303   691.4   322.4   691.4   332.1   691.4
   351.6  692.24     439  698.66   497.3  702.02     507  702.46   536.2  702.73
   545.9     703   555.6  703.66   565.4  704.82   575.1  706.73   584.8  709.12
#Mann= 3 , 0 , 0
       0     .06       0   293.2    .045       0   322.4     .07       0
Bank Sta=293.2,322.4
XS Rating Curve= 0 ,0
Exp/Cntr=0.3,0.1

Type RM Length L Ch R = 1 ,30208.2 ,125.8,126.6,127.4
XS GIS Cut Line= 4
     1473211.503      308476.808     1473475.392       308699.03
     1473652.475      308841.391       1473918.1      309058.405
#Sta/Elev= 30
       0  733.29    38.3  732.82    86.2  731.01   105.4   730.1     115  729.45
   182.1  724.11   201.2  722.25   220.4  719.96   268.3  713.36   306.7  707.48
   316.2  706.43   325.8   705.6   373.4  702.29   401.8  701.29   411.3  700.52
   430.2  698.62   439.7   697.9   468.1  696.53   534.3  691.65   553.3   691.4
   562.7  691.63   572.2   692.5     582  693.74   640.8  696.18   719.2  700.62
   758.4  703.34   836.8  707.27   856.4  708.68   895.6  712.38   915.2  713.37
#Mann= 3 , 0 , 0
       0     .06       0   534.3    .045       0   562.7     .05       0
#XS Ineff= 2 , 0
                          601.56          697.87
Permanent Ineff=
       F       F
Bank Sta=534.3,562.7
XS Rating Curve= 0 ,0
Exp/Cntr=0.3,0.1

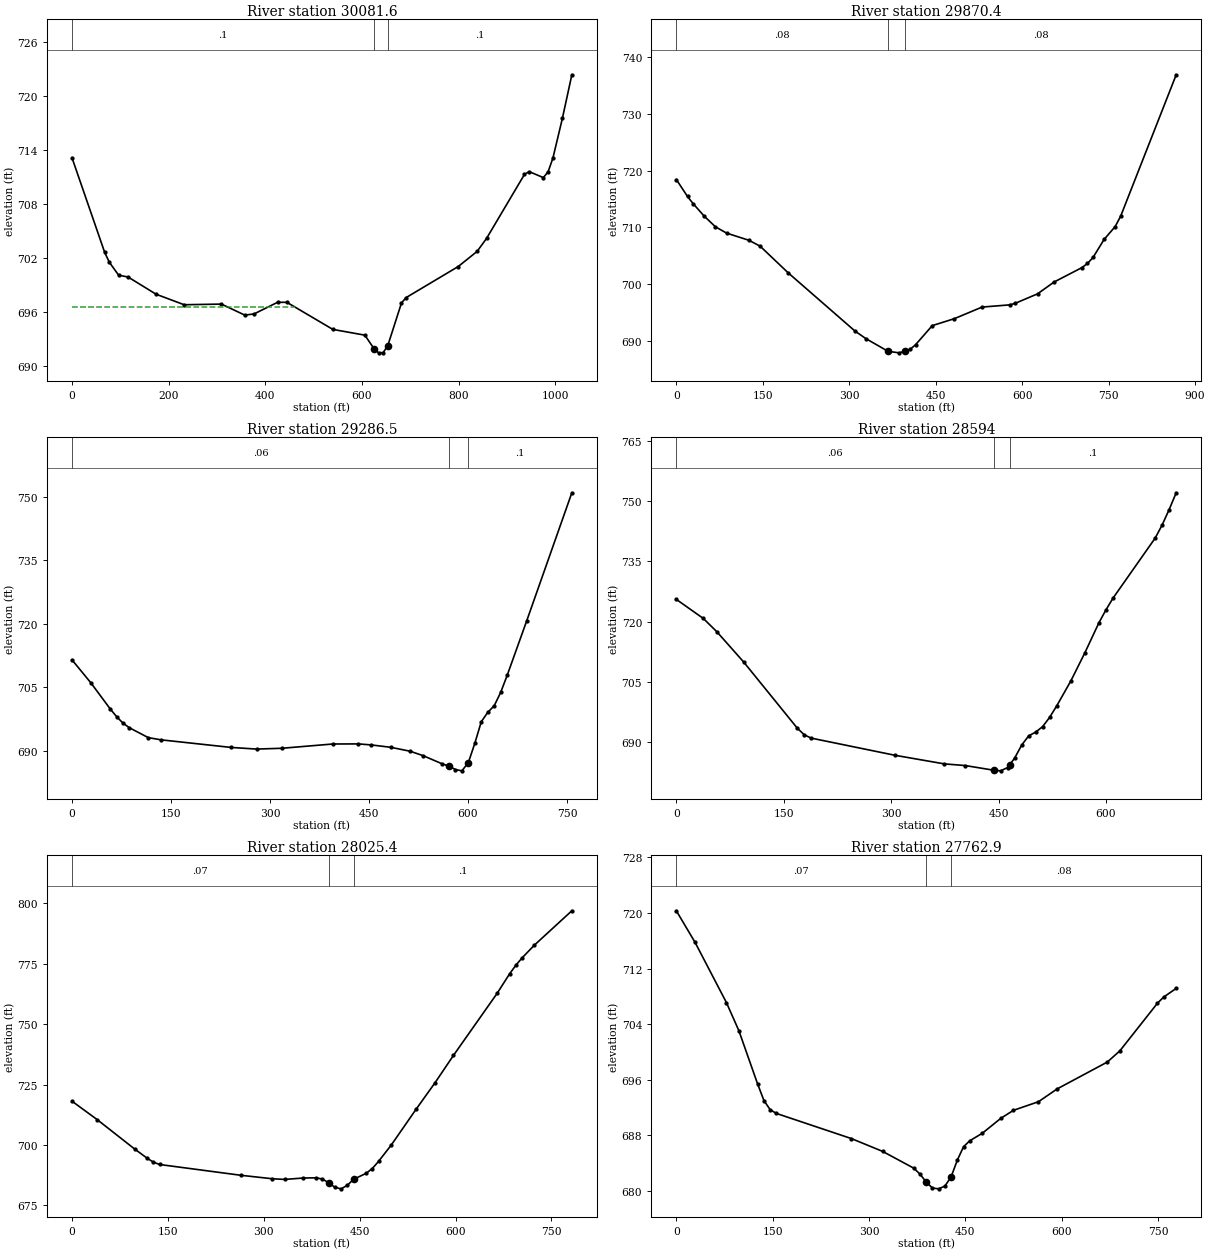
Type RM Length L Ch R = 1 ,30081.6 ,220.9,211.2,188.6
XS GIS Cut Line= 4
     1473010.114      308690.349     1473451.086      308834.446
     1473628.169      308976.808     1473893.794      309193.821
#Sta/Elev= 30
       0  713.16    67.6  702.62    77.3  701.51    96.6  700.07     116  699.87
     174  697.95     232  696.78   309.3  696.85   357.6  695.62   376.9  695.76
   425.3  697.05   444.6  697.05   539.7  694.03   605.9  693.39   624.9  691.88
   634.3  691.42   643.8  691.44   653.3  692.22   681.7  696.98   691.1  697.57
   798.9  701.03   838.1  702.72   857.7  704.17   936.1   711.3   945.9  711.61
   975.3  710.94   985.1  711.61   994.9  713.11  1014.5  717.53  1034.1   722.4
#Mann= 3 , 0 , 0
       0      .1       0   624.9    .045       0   653.3      .1       0
#XS Ineff= 2 , 0
          461.65  696.52
Permanent Ineff=
       F       F
Bank Sta=624.9,653.3
XS Rating Curve= 0 ,0
Exp/Cntr=0.3,0.1

Type RM Length L Ch R = 1 ,29870.4 ,575.4,583.9,603.1
XS GIS Cut Line= 4
     1473069.576      308894.559     1473323.048      308960.532
     1473525.443      309069.778     1473835.201      309281.712
#Sta/Elev= 30
       0  718.43    19.4  715.45    29.1   714.2    48.5  711.98    67.9  710.12
    87.3  709.01   126.1  707.75   145.5  706.71     194  702.04   309.8  691.82
     329  690.47   367.3  688.25   386.5  687.98   396.1  688.25   405.7   688.6
   415.2  689.42     444  692.76   482.3  693.98   530.4  696.02   578.5  696.41
   588.2  696.69   626.6  698.34   655.5  700.43   703.6  702.95   713.3  703.68
   722.9  704.73   742.1   707.9   761.4  710.17     771  712.02   867.2  736.83
#Mann= 3 , 0 , 0
       0     .08       0   367.3    .045       0   396.1     .08       0
Bank Sta=367.3,396.1
XS Rating Curve= 0 ,0
Exp/Cntr=0.3,0.1

Type RM Length L Ch R = 1 ,29286.5 ,686.3,692.5,697.8
XS GIS Cut Line= 3
     1472945.474      309122.246     1473306.002       309345.77
      1473576.52      309540.393
#Sta/Elev= 30
       0  711.45    28.9  705.96    57.8  699.88    67.5  698.05    77.1  696.53
    86.8  695.42   115.7  693.07     135  692.55     241  690.76   279.6  690.37
   318.2  690.56   395.3  691.57     434  691.59   453.6  691.35     483  690.79
   512.4  689.86     532  688.82   561.4  686.85   571.2  686.35     581  685.54
   590.8  685.23   600.6  687.18   610.4  691.74   620.2  696.83     630  699.04
   639.8  700.61   649.6  703.76   659.4  707.77   688.8  720.56   757.4   750.9
#Mann= 3 , 0 , 0
       0     .06       0   571.2    .045       0   600.6      .1       0
Bank Sta=571.2,600.6
XS Rating Curve= 0 ,0
Exp/Cntr=0.3,0.1

Type RM Length L Ch R = 1 ,28594   ,574.5,568.6,562.1
XS GIS Cut Line= 3
     1472666.798      309601.157     1472819.576      309710.532
     1473147.701      310101.157
#Sta/Elev= 30
       0  725.52    37.6  720.79    56.4  717.51      94  709.95   169.1  693.44
   178.5  691.86   187.9  691.02   305.6  686.72   374.3  684.59   403.7  684.17
     443  683.02   452.8  682.86   462.6  683.68   465.6   684.4   472.4  686.02
   482.2  689.25     492  691.56   501.8   692.5   511.6  693.88   521.4   696.2
   531.3  699.06   550.9  705.23   570.5  712.24   590.1   719.7   599.9  722.91
   609.8  725.84   668.6  740.76   678.4  744.04   688.2  747.88     698  752.05
#Mann= 3 , 0 , 0
       0     .06       0     443    .045       0   465.6      .1       0
Bank Sta=443,465.6
XS Rating Curve= 0 ,0
Exp/Cntr=0.3,0.1

Type RM Length L Ch R = 1 ,28025.4 ,246.1,262.4,278.7
XS GIS Cut Line= 3
     1472396.495      309970.123     1472837.493      310261.635
     1473048.742      310401.504
#Sta/Elev= 30
       0  718.13    39.2  710.54    97.9  698.35   117.5  694.53   127.3   692.9
     137  691.91   264.3  687.44   313.3  686.01   332.8  685.73   362.2  686.32
   381.8  686.39   391.6   685.9   401.4  684.38   411.2  682.46     421  681.83
   430.7  683.28   440.5  685.78   460.1  688.23   469.9  690.25   479.7  693.23
   499.3  699.89   538.4  714.81   567.6  725.62   596.8  737.08   665.1  762.77
   684.6  770.85   694.3  774.37     704  777.42   723.5  782.77     782  796.97
#Mann= 3 , 0 , 0
       0     .07       0   401.4    .045       0   440.5      .1       0
Bank Sta=401.4,440.5
XS Rating Curve= 0 ,0
Exp/Cntr=0.3,0.1

Type RM Length L Ch R = 1 ,27762.9 ,823.1,814.7,804.9
XS GIS Cut Line= 4
     1472361.242      310003.934     1472509.556      310209.304
     1472573.048       310443.17     1472600.826       310724.42
#Sta/Elev= 30
       0  720.32    29.2  715.77      78  707.11    97.4  703.06   126.7  695.36
   136.4  693.01   146.2  691.68   155.9  691.15   272.7  687.53   321.2  685.69
   369.6  683.28   379.3  682.43     389  681.29   398.7  680.42   408.4   680.3
   418.1  680.69   427.8  682.01   437.5  684.43   447.2  686.36   456.9  687.22
   476.3  688.29   505.4  690.46   524.9   691.6   563.9  692.84   593.1  694.69
   671.1  698.55   690.6  700.16     749     707   758.8   707.9   778.3  709.15
#Mann= 3 , 0 , 0
       0     .07       0     389    .045       0   427.8     .08       0
Bank Sta=389,427.8
XS Rating Curve= 0 ,0
Exp/Cntr=0.3,0.1