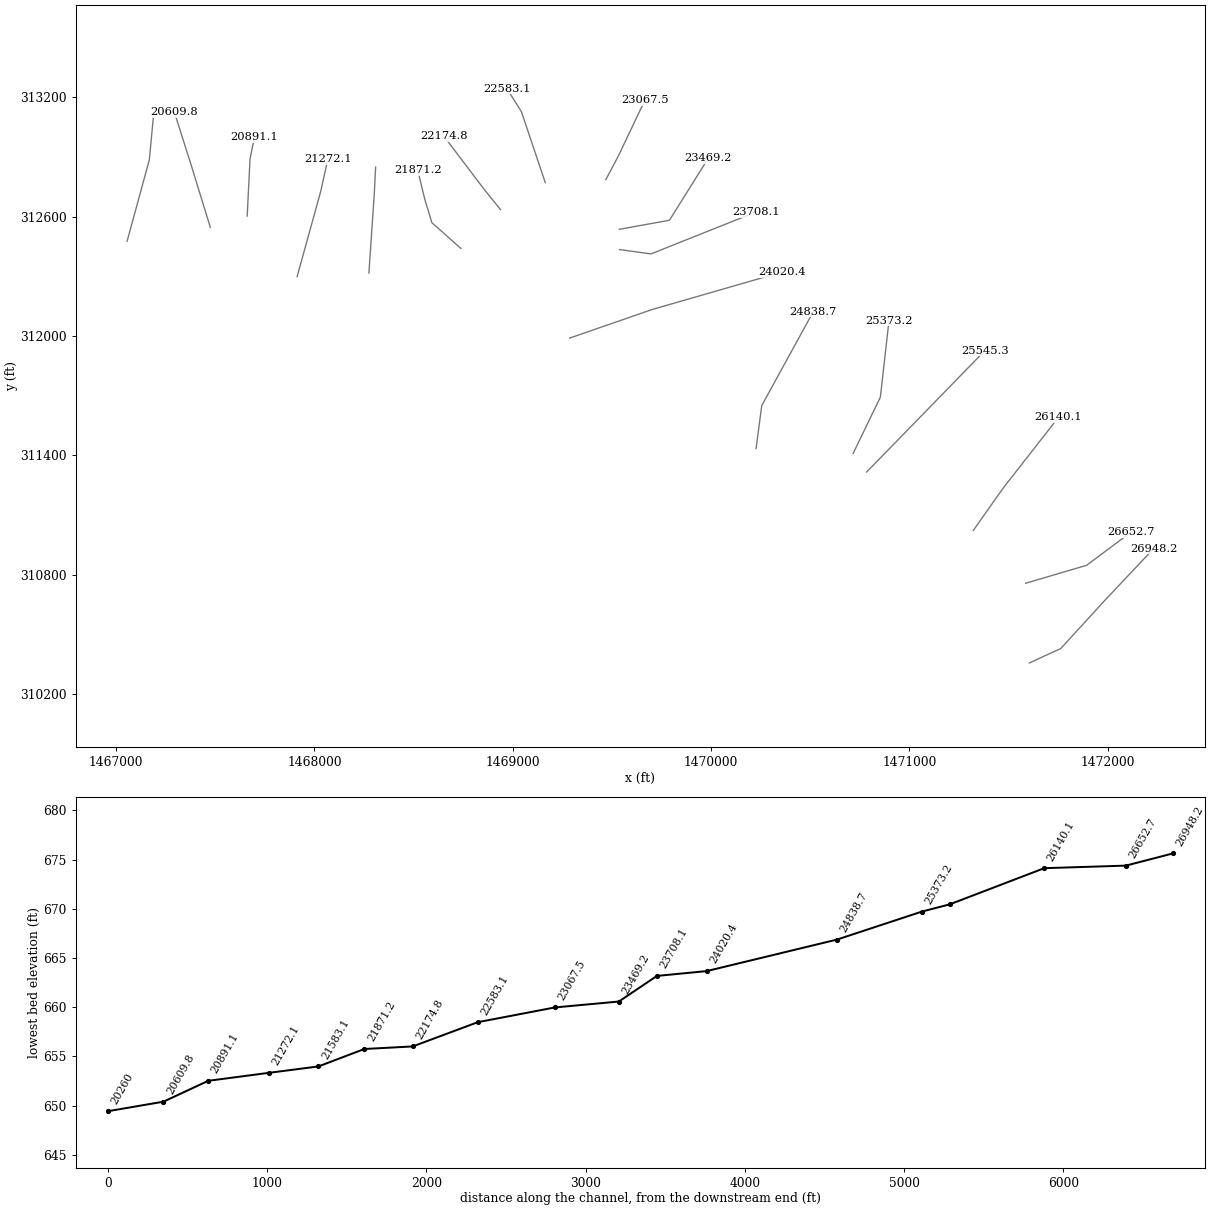
HEC-RAS study CowCr.prj: CowCr

--- CowCr.g01 (geometry) --- (continued)

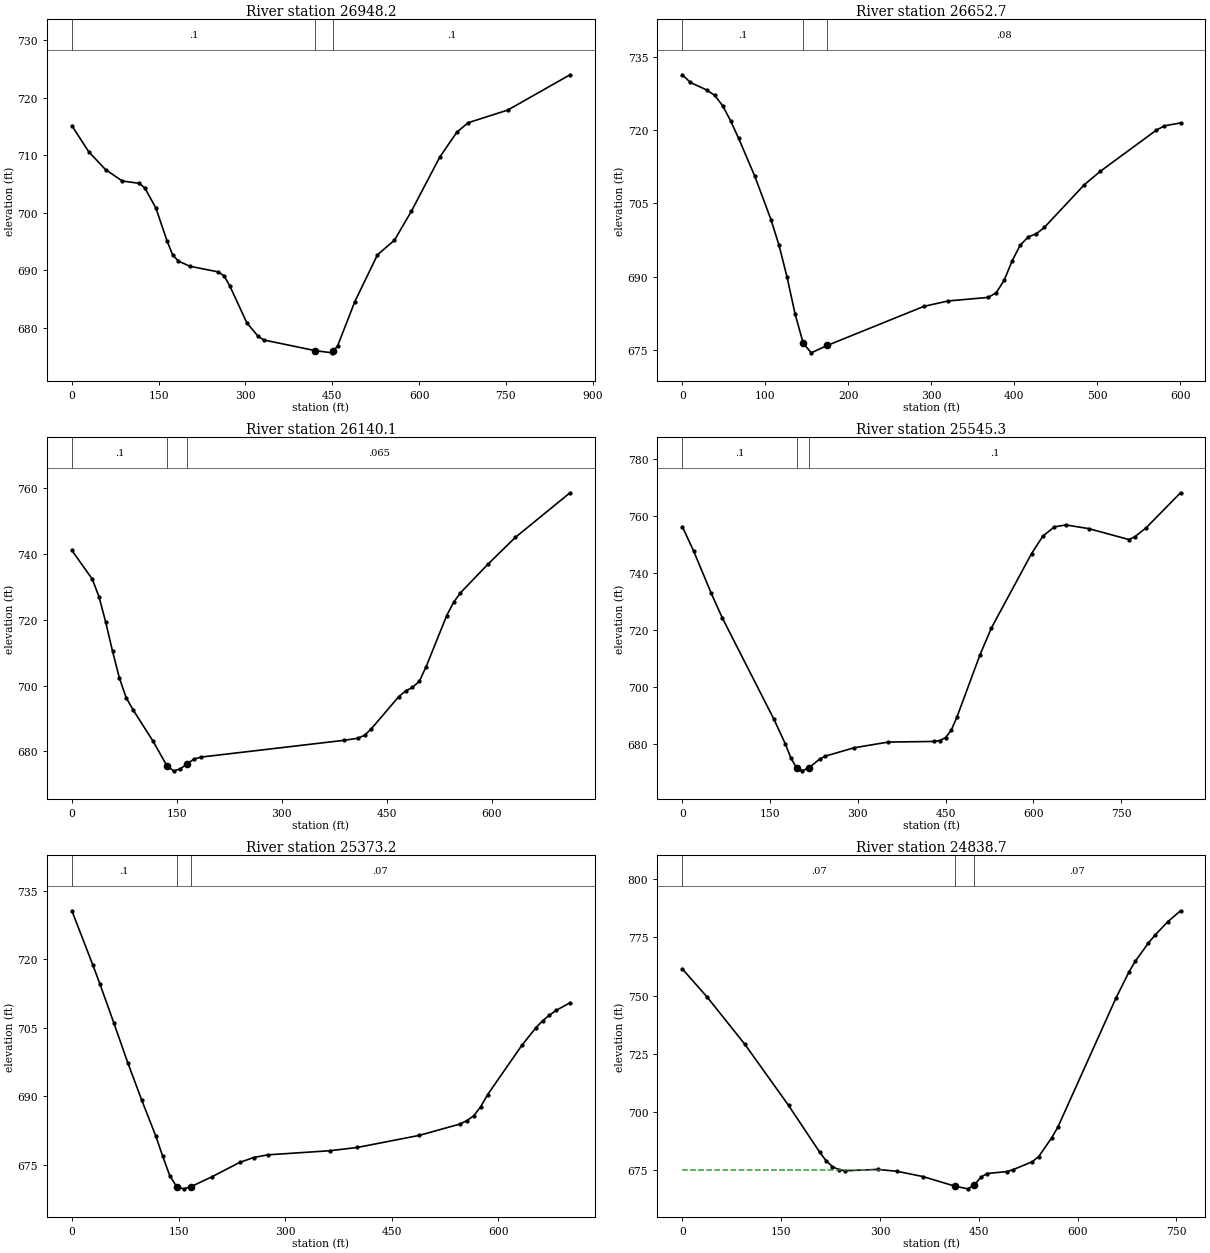
Type RM Length L Ch R = 1 ,26948.2 ,308.1,295.5,282.9
XS GIS Cut Line= 4
     1471604.298      310356.365     1471762.933      310428.827
     1471988.979      310674.932     1472231.034      310931.018
#Sta/Elev= 30
       0  715.13    29.1   710.6    58.1   707.5    87.2  705.51   116.3  705.11
     126  704.32   145.3  700.78   164.7  695.01   174.4  692.62   184.2  691.58
   203.9  690.68     253   689.7   262.9  689.01   272.7  687.31   302.2  680.87
   321.8  678.49   331.6  677.86   420.1  676.01   449.6  675.62  451.97675.9223
   459.4  676.87   488.9  684.51   528.1  692.67   557.5  695.22   586.9  700.29
   635.8  709.67   665.2  713.99   684.8  715.65   753.3  717.85   860.9  723.99
#Mann= 3 , 0 , 0
       0      .1       0   420.1    .045       0  451.97      .1       0
Bank Sta=420.1,451.97
XS Rating Curve= 0 ,0
Exp/Cntr=0.3,0.1

Type RM Length L Ch R = 1 ,26652.7 ,497.2,512.6,527.7
XS GIS Cut Line= 3
     1471586.069      310756.973      1471893.36       310847.25
     1472118.136      311014.445
#Sta/Elev= 30
       0   731.3     9.7  729.72    29.1  728.21    38.8  727.11    48.5  724.99
    58.2  721.86    67.9  718.26    87.4  710.48   106.8  701.65   116.5  696.39
   126.2  689.86   135.9  682.31   145.6  676.38   155.3  674.38   174.7   675.9
   291.2   683.9   320.3     685   368.6  685.73   378.2  686.67   387.9  689.25
   397.6  693.26   407.2  696.42   416.9  698.12   426.5  698.74   436.2  700.04
   484.5   708.8   503.8  711.55   571.4  719.98   581.1  720.85   600.4  721.44
#Mann= 3 , 0 , 0
       0      .1       0   145.6    .045       0   174.7     .08       0
Bank Sta=145.6,174.7
XS Rating Curve= 0 ,0
Exp/Cntr=0.3,0.1

Type RM Length L Ch R = 1 ,26140.1 ,598.2,594.8,591.2
XS GIS Cut Line= 3
      1471322.18      311022.598     1471473.222      311236.139
     1471750.999      311590.306
#Sta/Elev= 30
       0  741.13    29.1  732.42    38.8     727    48.4  719.25    58.1  710.47
    67.8  702.38    77.5   696.4    87.2  692.74   116.2  683.05   135.6  675.71
   145.3  674.12     155  674.72   164.7  676.27   174.4  677.68   184.1  678.29
   388.8   683.4   408.3  684.01   418.1  684.92   427.9  686.92     467  696.68
   476.8   698.4   486.6   699.5   496.4  701.35   506.2  705.82   535.5  721.32
   545.3  725.32   555.1  728.22   594.2  736.89   633.4  745.06   711.7  758.65
#Mann= 3 , 0 , 0
       0      .1       0   135.6    .045       0   164.7    .065       0
Bank Sta=135.6,164.7
XS Rating Curve= 0 ,0
Exp/Cntr=0.3,0.1

Type RM Length L Ch R = 1 ,25545.3 ,164.6,172,179.2
XS GIS Cut Line= 3
      1470784.24      311316.318     1471023.569      311560.792
     1471379.472      311925.375
#Sta/Elev= 30
       0  756.18    19.6  747.48    48.9     733    68.4   724.1   156.4   688.6
     176  679.92   185.7  674.86   195.5  671.43   205.3  670.44   216.7  671.56
   234.6  674.56   244.4   675.6   293.2  678.52   351.9  680.54   430.3  680.76
   440.1  681.09   449.9  682.08   459.7  684.73   469.5  689.38   508.7  711.13
   528.3  720.61   596.9  746.71   616.5  752.92   636.1  756.11   655.7  756.79
   694.8  755.49   763.4  751.66   773.2  752.59   792.8  755.77   851.6  768.08
#Mann= 3 , 0 , 0
       0      .1       0   195.5    .045       0   216.7      .1       0
Bank Sta=195.5,216.7
XS Rating Curve= 0 ,0
Exp/Cntr=0.3,0.1

Type RM Length L Ch R = 1 ,25373.2 ,535.7,534.5,533.3
XS GIS Cut Line= 3
     1470716.277       311409.75      1470853.43      311692.736
     1470896.833      312076.417
#Sta/Elev= 30
       0  730.59    29.5  718.71    39.3  714.62      59  706.04    78.6  697.33
    98.3  689.11   117.9  681.32   127.8  676.82   137.6  672.63   147.4  670.17
   157.2  669.72   167.1  670.17   196.5  672.32   235.8  675.49   255.5  676.57
   275.2  677.16   362.7  678.06   401.4  678.78   488.2  681.41   546.2  683.92
   555.8  684.68   565.4  685.74   575.1  687.74   584.8  690.37     633  701.17
   652.3  704.93     662  706.51   671.6  707.74   681.3   708.8   700.6  710.46
#Mann= 3 , 0 , 0
       0      .1       0   147.4    .045       0   167.1     .07       0
Bank Sta=147.4,167.1
XS Rating Curve= 0 ,0
Exp/Cntr=0.3,0.1

Type RM Length L Ch R = 1 ,24838.7 ,835.2,818.3,800.8
XS GIS Cut Line= 3
     1470226.694      311434.056      1470255.34      311650.202
     1470514.888      312121.556
#Sta/Elev= 30
       0  761.43    37.9  749.24    94.8  729.04   161.2  702.74   208.6  682.56
     218  679.01   227.8  676.44   237.6  675.08   247.4  674.64   296.3  675.23
   325.6  674.42   364.8  672.17   413.7  668.02   433.3  666.87   443.1   668.5
   452.8   671.8   462.6  673.46     492  674.27   501.8  675.09   531.1  678.54
   540.9  680.75   560.5  688.78   570.2  693.58   658.3  749.01   677.9  760.14
   687.6   764.8   707.2  772.52     717  775.83   736.6   781.7   756.1  786.44
#Mann= 3 , 0 , 0
       0     .07       0   413.7    .045       0   443.1     .07       0
#XS Ineff= 2 , 0
          306.28  675.06
Permanent Ineff=
       F       F
Bank Sta=413.7,443.1
XS Rating Curve= 0 ,0
Exp/Cntr=0.3,0.1

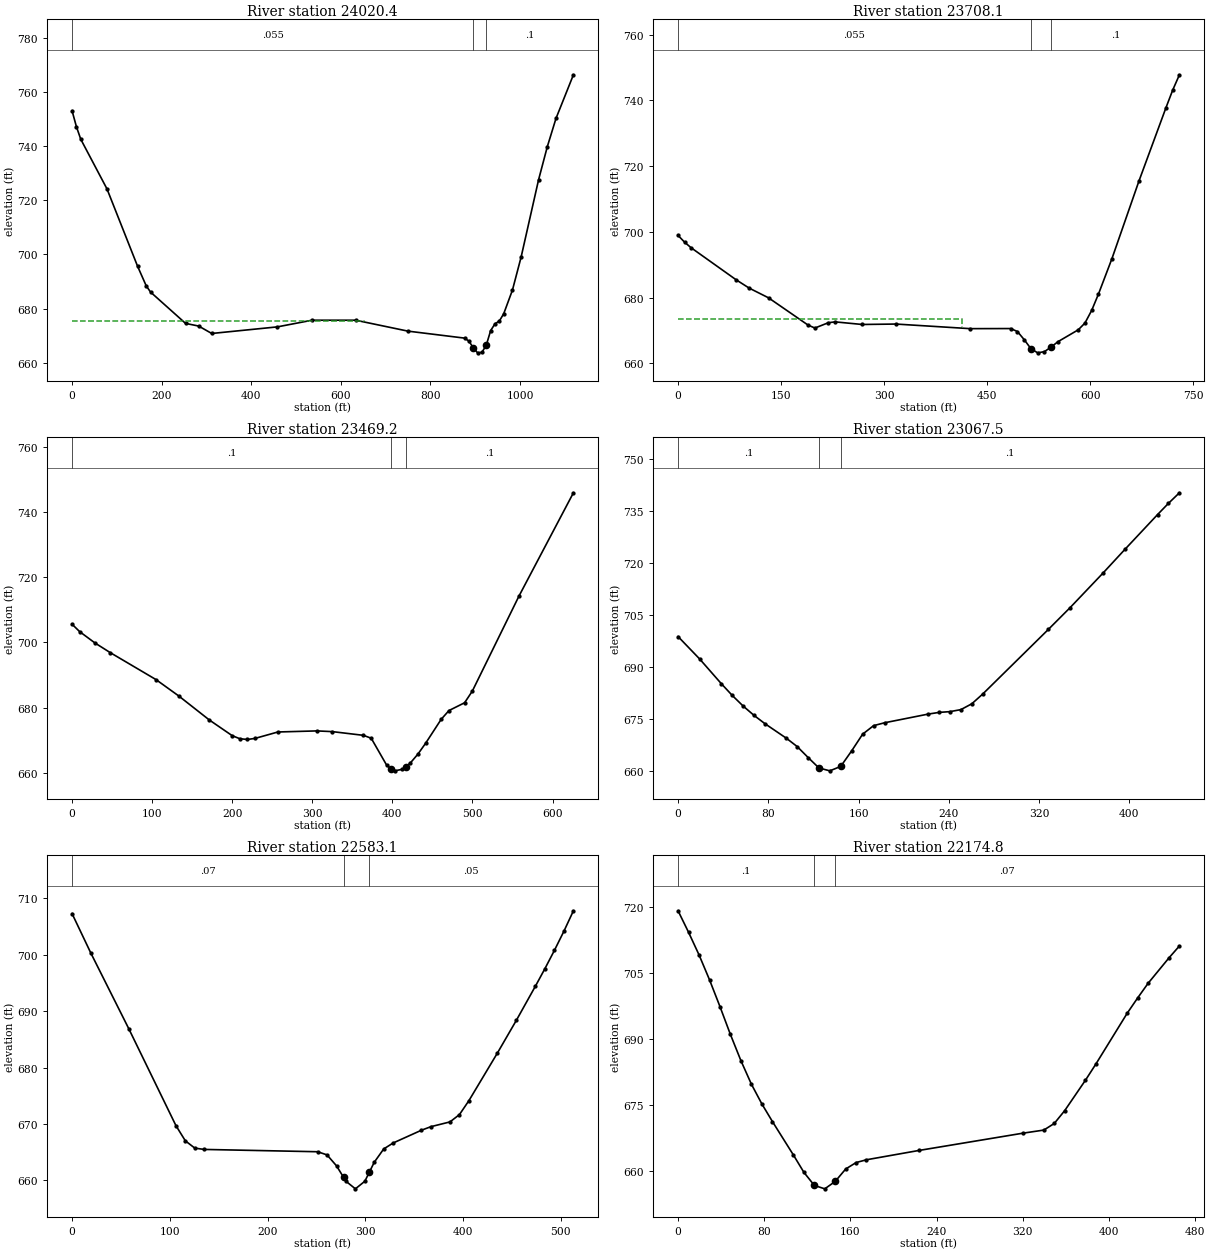
Type RM Length L Ch R = 1 ,24020.4 ,310.3,312.3,314.5
XS GIS Cut Line= 3
      1469286.59      311989.177     1469701.086      312132.407
     1470355.166      312320.341
#Sta/Elev= 30
       0  753.08     9.8  747.15    19.5  742.53      78   724.2   146.2  695.67
   165.7  688.36   175.4  686.08   253.4  674.54   282.6  673.56   311.8  670.82
     458  673.25   535.8  675.72     633  675.72   749.6  671.69     876  669.11
   885.8  668.01   895.5  665.56   905.2  663.67   914.9  663.84   924.6   666.5
   934.4   671.9   944.1   674.4   953.8  675.43   963.5   678.1     983  686.84
  1002.4  699.06  1041.3  727.56  1060.8  739.78  1080.2  750.23  1119.1  766.35
#Mann= 3 , 0 , 0
       0    .055       0   895.5    .045       0   924.6      .1       0
#XS Ineff= 2 , 0
          652.41  675.34
Permanent Ineff=
       F       F
Bank Sta=895.5,924.6
XS Rating Curve= 0 ,0
Exp/Cntr=0.3,0.1

Type RM Length L Ch R = 1 ,23708.1 ,224.6,238.9,253.3
XS GIS Cut Line= 3
     1469538.326      312434.056     1469696.746      312412.354
      1470226.26      312622.858
#Sta/Elev= 30
       0  698.91     9.4  696.88    18.8  695.19    84.6   685.4   103.5  682.88
   131.7  679.92   189.4   671.6   199.2  670.73   218.8  672.35   228.7   672.6
     268  671.81   317.1  671.94   425.2  670.54   484.1  670.57   493.9  669.67
   503.8  667.19   513.6  664.44   523.4  663.18   533.2  663.54   543.1  664.97
   552.9  666.57   582.4  670.18   592.2  672.24     602  676.09   611.8  681.02
   631.5  691.85   670.8  715.46   710.1  737.76   719.9  743.12   729.7  747.79
#Mann= 3 , 0 , 0
       0    .055       0   513.6    .045       0   543.1      .1       0
#XS Ineff= 2 , 0
          413.26  673.39
Permanent Ineff=
       F       F
Bank Sta=513.6,543.1
XS Rating Curve= 0 ,0
Exp/Cntr=0.3,0.1

Type RM Length L Ch R = 1 ,23469.2 ,399.6,401.7,403.8
XS GIS Cut Line= 3
     1469536.866      312535.907     1469789.904       312581.48
     1469986.085       312893.98
#Sta/Elev= 30
       0   705.6     9.5  703.32    28.6  699.84    47.6  696.89   104.8   688.6
   133.3  683.56   171.4   676.2     200  671.38   209.5  670.44     219  670.21
   228.5  670.54   257.1  672.51   305.7  672.84   325.1  672.62   363.9  671.48
   373.6  670.59     393  662.27  397.99  661.29   402.8  660.58   412.5  661.05
   416.7  661.86   422.2  662.92   431.9  665.71   441.6  669.07     461  676.41
   470.7  679.09   490.2  681.48   499.9  685.08   558.1  714.23   626.1  745.95
#Mann= 3 , 0 , 0
       0      .1       0  397.99    .045       0   416.7      .1       0
#XS Ineff= 2 , 0
          325.85  672.55
Permanent Ineff=
       F       F
Bank Sta=397.99,416.7
XS Rating Curve= 0 ,0
Exp/Cntr=0.3,0.1

Type RM Length L Ch R = 1 ,23067.5 ,465.5,484.4,501.8
XS GIS Cut Line= 3
     1469469.315      312786.052     1469532.528      312904.813
      1469665.93       313184.49
#Sta/Elev= 30
       0  698.74    19.2  692.25    38.4  685.12      48  681.76    57.7  678.68
    67.3     676    76.9  673.62    96.1  669.37   105.7  666.96   115.3  663.82
   124.9  660.81   134.5  659.98   144.2  661.26   153.9  665.75   163.6  670.56
   173.3  673.02     183  673.85   221.7  676.36   231.4  676.85     241  677.07
   250.7  677.65   260.4  679.34   270.1  682.16   328.2  700.79   347.6  707.12
   376.6  717.04     396  723.87     425  733.94   434.7   737.2   444.4  740.24
#Mann= 3 , 0 , 0
       0      .1       0   124.9    .045       0   144.2      .1       0
Bank Sta=124.9,144.2
XS Rating Curve= 0 ,0
Exp/Cntr=0.3,0.1

Type RM Length L Ch R = 1 ,22583.1 ,400.3,408.3,415.2
XS GIS Cut Line= 3
     1469163.847      312770.427     1469043.404      313127.415
     1468970.704      313242.433
#Sta/Elev= 30
       0   707.3    19.3  700.27      58  686.89   106.3  669.68   115.9  666.99
   125.6   665.7   135.2  665.47   251.2  665.06   260.8   664.5   270.5  662.56
  277.79660.5008   280.2  659.82   289.8  658.48   299.5  659.83  304.02661.4167
   309.1   663.2   318.8  665.56   328.5  666.62   357.4  668.88   367.1  669.51
   386.5  670.35   396.2  671.64   405.9  674.12   435.1  682.58   454.5  688.39
     474  694.45   483.7  697.55   493.4  700.79   503.1  704.18   512.8   707.8
#Mann= 3 , 0 , 0
       0     .07       0  277.79    .045       0  304.02     .05       0
Bank Sta=277.79,304.02
XS Rating Curve= 0 ,0
Exp/Cntr=0.3,0.1

Type RM Length L Ch R = 1 ,22174.8 ,312.2,303.6,295.4
XS GIS Cut Line= 3
     1468937.501      312635.662     1468851.902      312741.625
     1468652.779      313003.717
#Sta/Elev= 30
       0  719.25     9.7  714.39    19.5  709.21    29.2  703.56    38.9  697.47
    48.6  691.13    58.4  685.14    68.1  679.81    77.8  675.33    87.6  671.32
     107  663.75   116.8  659.78   126.5   656.8   136.2  656.02   145.9  657.71
   155.6  660.53   165.3     662   174.9  662.63   223.4  664.74   320.2  668.68
   339.5  669.38   349.2  670.88   358.9   673.8   378.2  680.73   387.9  684.42
     417  695.98   426.6  699.42   436.3  702.75   455.7  708.54   465.4  711.25
#Mann= 3 , 0 , 0
       0      .1       0   126.5    .045       0   145.9     .07       0
Bank Sta=126.5,145.9
XS Rating Curve= 0 ,0
Exp/Cntr=0.3,0.1

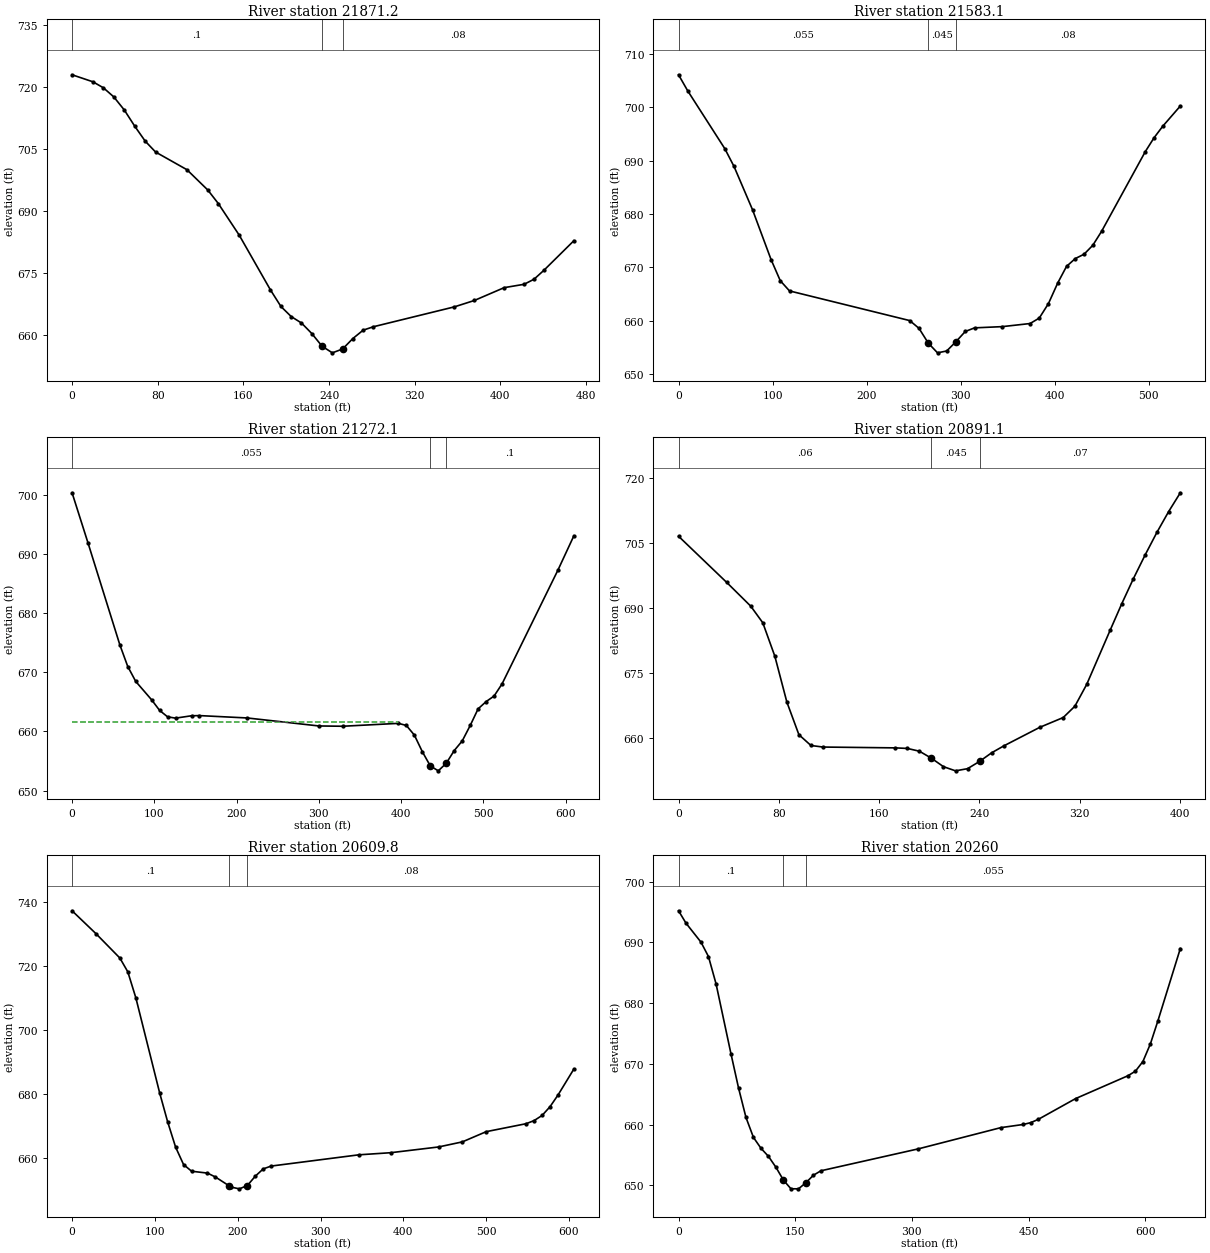
Type RM Length L Ch R = 1 ,21871.2 ,296.2,288.1,280
XS GIS Cut Line= 4
     1468738.065      312440.132     1468591.874        312569.3
     1468555.774       312688.83     1468520.617      312833.361
#Sta/Elev= 30
       0  723.07    19.5  721.37    29.3  719.91      39  717.71    48.8  714.54
    58.5  710.64    68.3  707.01      78  704.37   107.3  700.09   126.8  695.17
   136.6   691.9   156.1  684.26   185.3  670.99   195.1  666.98   204.7  664.54
   214.3  662.98   223.9  660.44   233.5  657.37   243.1  655.76   252.7  656.69
   262.3  659.23   271.9  661.25   281.5  662.08   357.1  666.89   375.7  668.43
   403.6  671.54   422.2  672.35   431.5  673.58   440.8  675.76   468.7   682.9
#Mann= 3 , 0 , 0
       0      .1       0   233.5    .045       0   252.7     .08       0
Bank Sta=233.5,252.7
XS Rating Curve= 0 ,0
Exp/Cntr=0.3,0.1

Type RM Length L Ch R = 1 ,21583.1 ,316.3,311,306.5
XS GIS Cut Line= 3
     1468274.524      312316.434     1468301.867      312718.778
     1468308.378      312848.986
#Sta/Elev= 30
       0  706.08     9.8  703.06    49.2  692.24      59  688.91    78.7  680.79
    98.4  671.46   108.2   667.5     118  665.59   245.9  660.03   255.7  658.58
   265.6  655.81   275.4  653.99   285.2  654.34   295.1   656.1   304.9  657.99
   314.8  658.67   344.3   658.9   373.8  659.48   383.6   660.5   393.4  663.23
   403.3   667.1   412.6  670.19   421.9  671.65   431.2  672.46   440.5  674.13
   449.8  676.73   496.4   691.7   505.7  694.29     515  696.46   533.6  700.23
#Mann= 3 , 0 , 0
       0    .055       0   265.6    .045       0   295.1     .08       0
Bank Sta=265.6,295.1
XS Rating Curve= 0 ,0
Exp/Cntr=0.3,0.1

Type RM Length L Ch R = 1 ,21272.1 ,374.8,381.1,386.1
XS GIS Cut Line= 3
     1467912.544      312298.205     1468031.675      312727.132
     1468067.492      312888.049
#Sta/Elev= 30
       0   700.3    19.4  691.82    58.1  674.61    67.7  670.96    77.4  668.44
    96.8  665.32   106.4  663.55   116.1  662.46   125.8  662.24   145.2  662.64
   154.8  662.67   212.9  662.27     300  660.92     329  660.87   396.8  661.36
   406.4     661   416.1  659.38   425.8  656.57   435.5  654.17   445.2  653.34
   454.9  654.62   464.6  656.77   474.3  658.39     484     661   493.6  663.81
   503.4  665.04     513  665.97   522.7  668.02   590.6  687.23     610  693.03
#Mann= 3 , 0 , 0
       0    .055       0   435.5    .045       0   454.9      .1       0
#XS Ineff= 2 , 0
           396.7  661.51
Permanent Ineff=
       F       F
Bank Sta=435.5,454.9
XS Rating Curve= 0 ,0
Exp/Cntr=0.3,0.1

Type RM Length L Ch R = 1 ,20891.1 ,273.3,281.3,288.9
XS GIS Cut Line= 3
     1467660.808      312602.459     1467675.131      312890.219
     1467697.701      313000.028
#Sta/Elev= 30
       0  706.67    38.4  696.02    57.6  690.53    67.2   686.7    76.8  678.99
    86.4   668.4      96  660.87   105.6  658.38   115.2  658.02   172.9  657.83
   182.5   657.7   192.1  657.06   201.7  655.44   211.3  653.49   220.9  652.53
   230.5  653.03   240.1  654.71   249.7  656.69   259.3  658.27   288.1  662.57
   306.8  664.83   316.1  667.44   325.5  672.46   344.2  684.96   353.5   691.1
   362.8   696.9   372.2  702.39   381.5  707.55   390.9  712.37   400.2   716.7
#Mann= 3 , 0 , 0
       0     .06       0   201.7    .045       0   240.1     .07       0
Bank Sta=201.7,240.1
XS Rating Curve= 0 ,0
Exp/Cntr=0.3,0.1

Type RM Length L Ch R = 1 ,20609.8 ,362.4,349.7,337
XS GIS Cut Line= 3
      1467474.61      312546.469     1467378.256      312858.969
     1467293.621      313124.594
#Sta/Elev= 30
       0  737.21    28.8  730.08    57.7  722.46    67.3  718.15      77  710.03
   105.8   680.3   115.4  671.32     125  663.43   134.6  657.99   144.3  655.91
   163.5  655.32   173.1   654.1  189.26651.4075   192.4  650.93     202  650.41
   211.6  651.44   221.2  654.36   230.8  656.64   240.4  657.52   346.2  661.03
   384.7  661.69   442.4  663.48   471.2  665.07     500  668.26   548.1  670.74
   557.7   671.7   567.4  673.31     577  676.04   586.6  679.67   605.8   687.8
#Mann= 3 , 0 , 0
       0      .1       0  189.26    .045       0   211.6     .08       0
Bank Sta=189.26,211.6
XS Rating Curve= 0 ,0
Exp/Cntr=0.3,0.1

Type RM Length L Ch R = 1 ,20260   ,229.8,229.7,228.7
XS GIS Cut Line= 3
      1467055.34      312476.157     1467167.319      312885.011
     1467188.152      313105.063
#Sta/Elev= 30
       0  695.19     9.6  693.15    28.9  690.02    38.5  687.65    48.2  683.18
    67.4  671.66    77.1  666.05    86.7  661.18    96.3   657.9     106  656.11
   115.6  654.78   125.2  652.99   134.9  650.86   144.5  649.45   154.2  649.44
   163.8  650.46   173.4  651.68     183  652.41   308.3  656.02   414.3  659.51
   443.1  660.03   452.7  660.33   462.4  660.87   510.4  664.29   577.7  668.05
   587.3   668.8   596.9  670.39   606.5  673.28   616.1  677.05     645  688.98
#Mann= 3 , 0 , 0
       0      .1       0   134.9    .045       0   163.8    .055       0
Bank Sta=134.9,163.8
XS Rating Curve= 0 ,0
Exp/Cntr=0.3,0.1