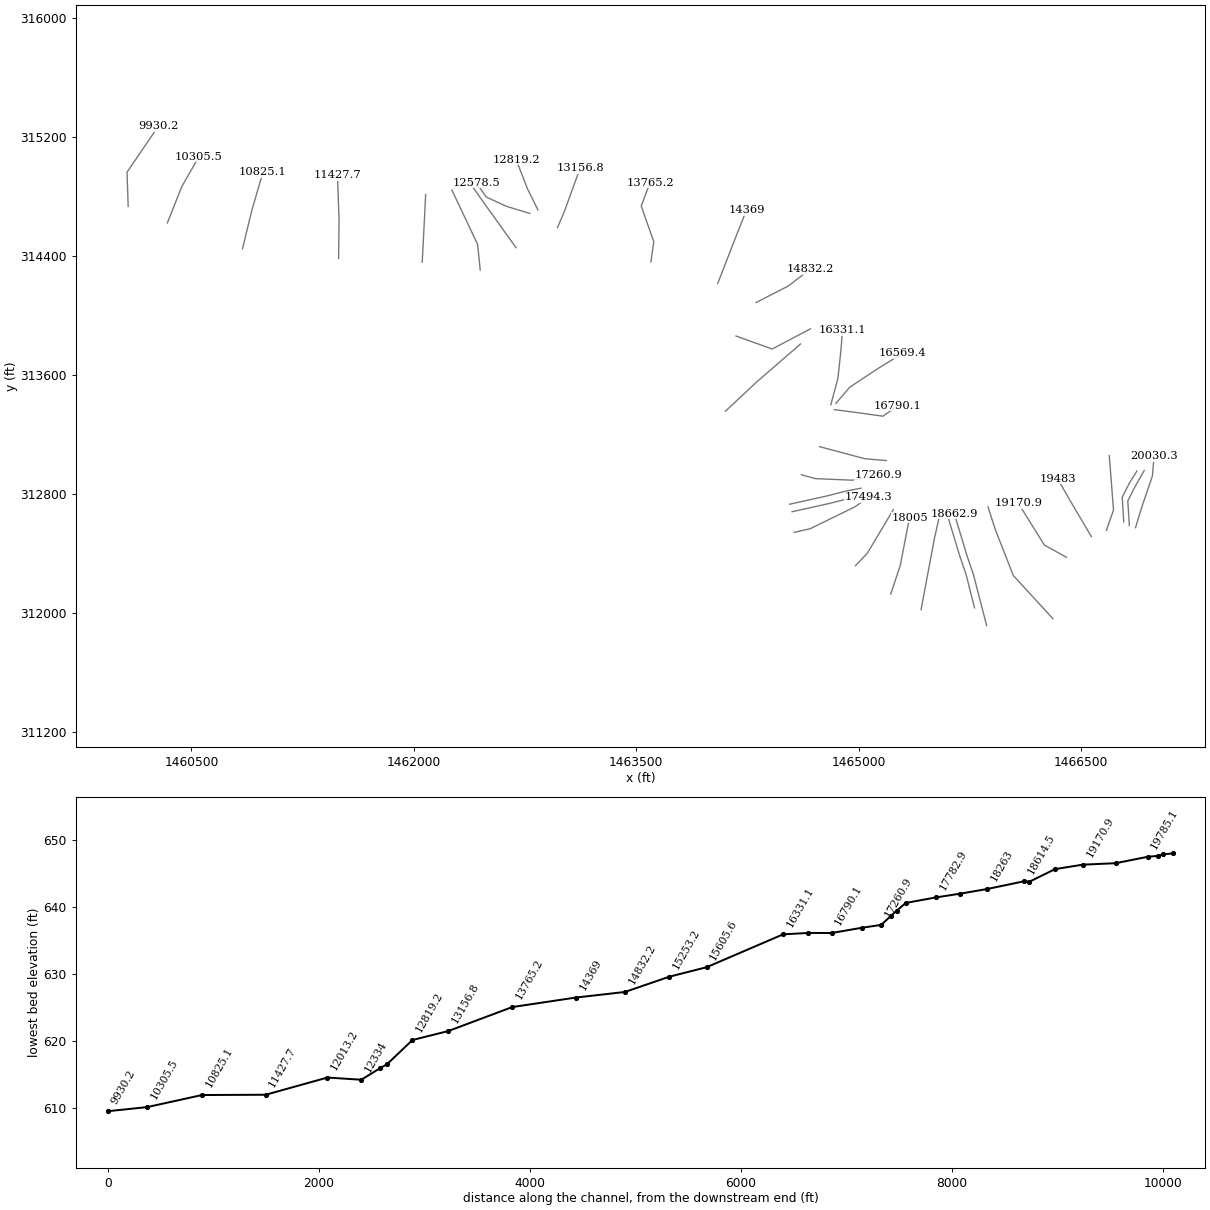
HEC-RAS study CowCr.prj: CowCr

--- CowCr.g01 (geometry) --- (continued)

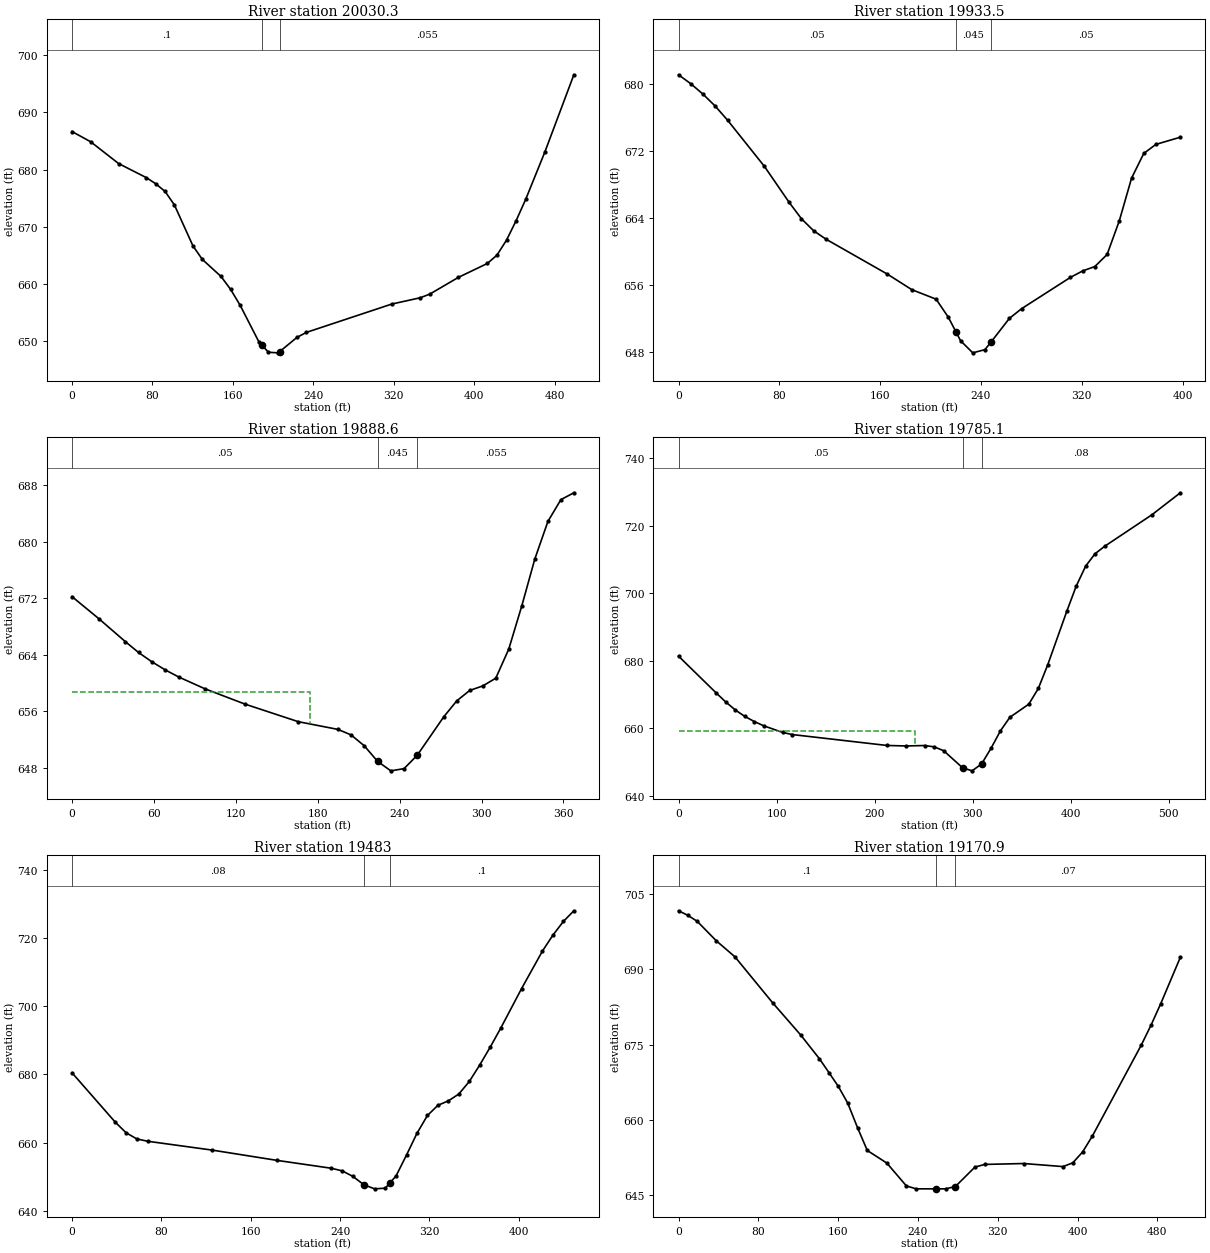
Type RM Length L Ch R = 1 ,20030.3 ,101.2,96.8,93.1
XS GIS Cut Line= 4
      1466867.84      312573.813     1466908.204      312706.625
     1466981.555       312920.91      1466992.84      313054.282
#Sta/Elev= 30
       0  686.66    18.5  684.88    46.3  681.07      74   678.6    83.3  677.53
    92.5   676.2   101.8  673.84   120.3  666.66   129.6  664.31   148.2  661.33
   157.7  659.08   167.1  656.33     186  649.85   189.1  649.27   195.4  648.08
   204.9  647.98  206.67648.2097   223.8  650.69   233.2  651.56   318.1  656.51
   346.4  657.61   355.9  658.25   384.4  661.18   413.1   663.6   422.7  665.06
   432.2  667.68   441.8   671.1   451.4  674.86   470.5  683.16   499.2  696.59
#Mann= 3 , 0 , 0
       0      .1       0   189.1    .045       0  206.67    .055       0
Bank Sta=189.1,206.67
XS Rating Curve= 0 ,0
Exp/Cntr=0.3,0.1

Type RM Length L Ch R = 1 ,19933.5 ,45,45,45
XS GIS Cut Line= 4
     1466826.173      312588.136     1466815.756        312753.5
     1466863.933      312848.552     1466926.433      312957.927
#Sta/Elev= 30
       0  681.12     9.8  680.04    19.5  678.79    29.2  677.36      39  675.67
    68.2  670.15    87.7  665.87    97.5   663.9   107.2  662.46     117  661.45
   165.7  657.27   185.1  655.41   204.4  654.27   214.1  652.11  220.02 650.395
   223.8   649.3   233.5  647.85   243.1  648.23  247.76649.1002   262.6  651.98
   272.3  653.14     311  656.88   320.7  657.65   330.4  658.18   340.1  659.62
   349.8  663.66   359.5  668.75   369.2  671.71   378.8  672.79   398.2  673.65
#Mann= 3 , 0 , 0
       0     .05       0  220.02    .045       0  247.76     .05       0
Bank Sta=220.02,247.76
XS Rating Curve= 0 ,0
Exp/Cntr=0.3,0.1

Type RM Length L Ch R = 1 ,19888.6 ,91,103.5,115.8
XS GIS Cut Line= 4
     1466788.413      312612.875     1466777.996       312778.24
     1466826.173      312873.292     1466876.954      312954.021
#Sta/Elev= 28
       0  672.21    19.5  669.12      39  665.87    48.7  664.33    58.5  663.01
    68.2  661.88      78  660.88    97.5  659.19   126.7  657.04   165.7  654.56
   194.8  653.47   204.4  652.69   214.1  651.15   223.8  648.96   233.5  647.62
   243.2  647.93   252.9  649.83   272.3  655.25   281.8   657.5   291.3  658.97
   300.9  659.61   310.4   660.7   319.9   664.8   329.5  670.94     339  677.53
   348.6  682.84   358.1  685.91   367.6  686.88
#Mann= 3 , 0 , 0
       0     .05       0   223.8    .045       0   252.9    .055       0
#XS Ineff= 2 , 0
          174.52  658.72
Permanent Ineff=
       F       F
Bank Sta=223.8,252.9
XS Rating Curve= 0 ,0
Exp/Cntr=0.3,0.1

Type RM Length L Ch R = 1 ,19785.1 ,291.7,302.1,312.4
XS GIS Cut Line= 3
     1466671.225      312555.584     1466719.402      312692.302
     1466690.756      313058.188
#Sta/Elev= 30
       0  681.41    38.7  670.44    48.3  667.81      58  665.47    67.6  663.58
    77.3  662.06      87  660.79   106.3  658.83     116  658.21   212.6  654.98
   231.9  654.83   251.2  654.96   260.9  654.56   270.5  653.43   289.8  648.38
   299.5  647.47   309.2   649.5   318.8  654.12   328.5  659.33   338.1  663.32
   357.4   667.2   367.1  671.84   376.8  678.92   396.1  694.64   405.7  702.08
   415.4  708.05     425  711.71   434.7   713.9     483  723.24     512  729.75
#Mann= 3 , 0 , 0
       0     .05       0   289.8    .045       0   309.2     .08       0
#XS Ineff= 2 , 0
          240.84  659.13
Permanent Ineff=
       F       F
Bank Sta=289.8,309.2
XS Rating Curve= 0 ,0
Exp/Cntr=0.3,0.1

Type RM Length L Ch R = 1 ,19483   ,311.6,312.1,312.3
XS GIS Cut Line= 3
     1466569.663      312513.917     1466421.952      312763.622
       1466343.1      312901.938
#Sta/Elev= 30
       0  680.48    38.7  666.03    48.4  662.93      58  661.13    67.7  660.45
   125.7  657.85   183.7  654.84   232.1  652.55   241.8  651.79   251.4  650.17
   261.1  647.76   270.8  646.52   280.4  646.71   284.7 648.302   290.1   650.3
   299.5  656.44   308.8  662.76   318.2     668   327.6  670.98     337  672.29
   346.3  674.27   355.7  677.96     365  682.76   374.4     688   383.8  693.55
   402.5  705.15   421.2  716.15   430.6  720.81     440  724.83   449.3  727.92
#Mann= 3 , 0 , 0
       0     .08       0   261.1    .045       0   284.7      .1       0
Bank Sta=261.1,284.7
XS Rating Curve= 0 ,0
Exp/Cntr=0.3,0.1

Type RM Length L Ch R = 1 ,19170.9 ,265.3,261.5,257.4
XS GIS Cut Line= 3
     1466401.694      312374.594     1466253.256      312456.625
     1466076.173      312739.177
#Sta/Elev= 30
       0  701.66     9.4  700.75    18.8  699.55    37.7  695.71    56.5   692.5
    94.2  683.37   122.5  676.92   141.3  672.18   150.8  669.44   160.2  666.69
   169.6  663.37   179.4  658.49   189.2  653.94   208.8  651.43   228.4  646.88
   238.2   646.3   257.9   646.3   267.7   646.3   277.5  646.76   297.1  650.63
   306.9  651.16   346.1  651.34   385.4  650.73   395.2  651.48     405  653.63
   414.8   656.8   463.8   674.9   473.6  678.87   483.4  683.18     503  692.39
#Mann= 3 , 0 , 0
       0      .1       0   257.9    .045       0   277.5     .07       0
Bank Sta=257.9,277.5
XS Rating Curve= 0 ,0
Exp/Cntr=0.3,0.1

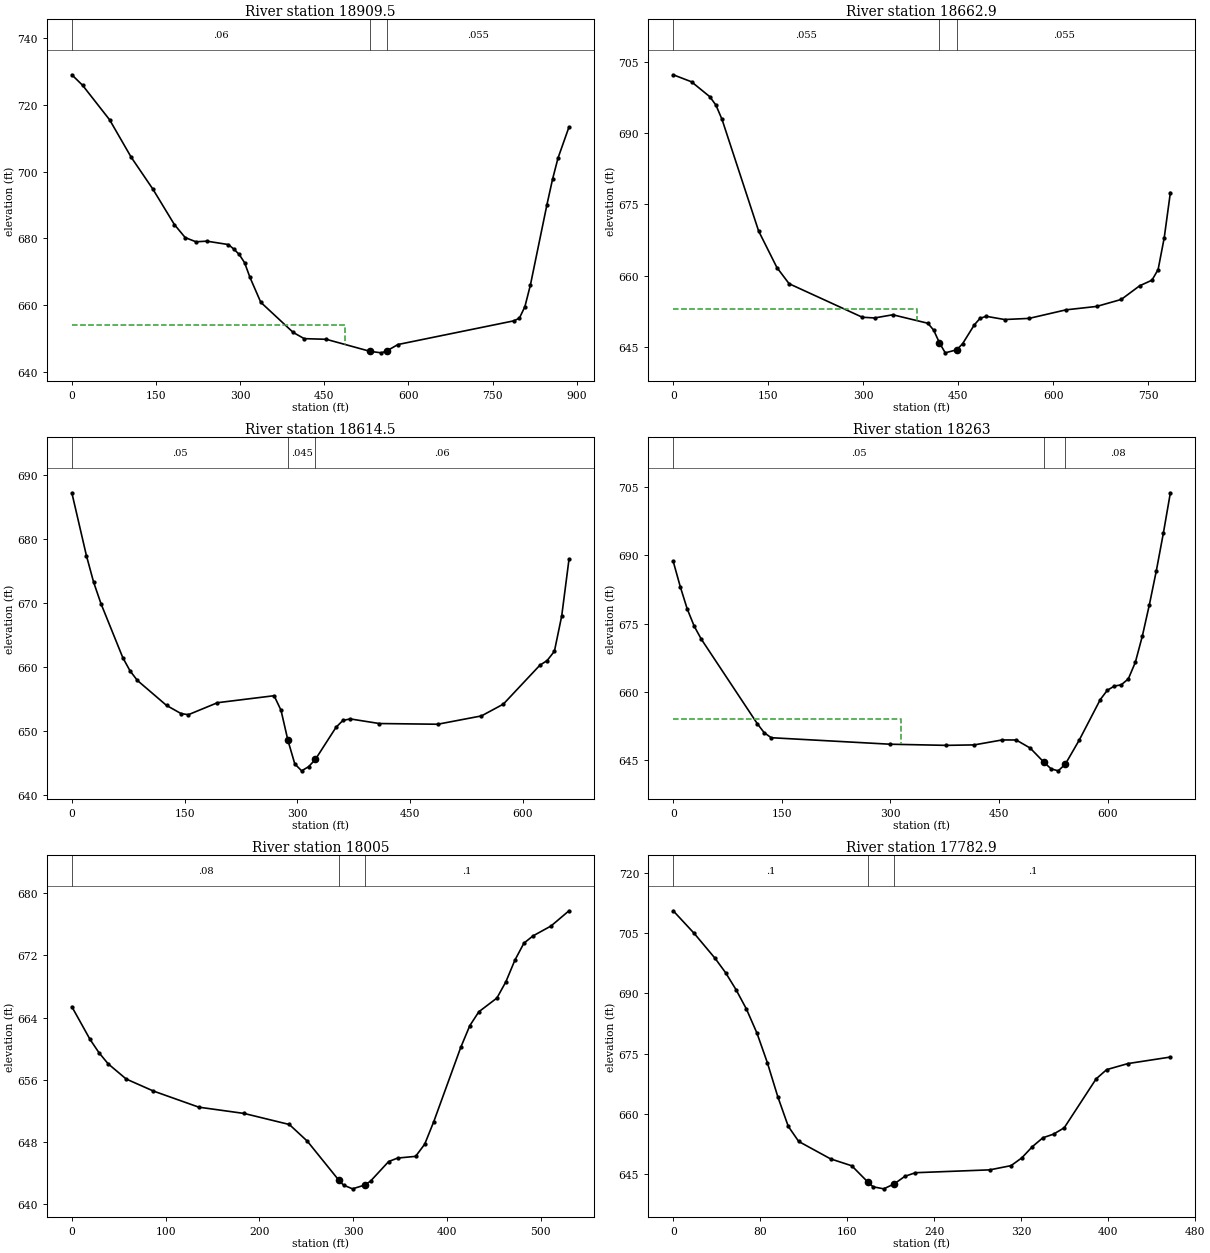
Type RM Length L Ch R = 1 ,18909.5 ,247.4,246.5,245.8
XS GIS Cut Line= 4
     1466310.548      311961.834       1466043.3       312252.06
     1465921.225      312563.396     1465873.048      312713.136
#Sta/Elev= 30
       0  729.05    19.2  725.89    67.4  715.53   105.8  704.32   144.3  694.79
   182.8  684.12   202.1  680.21   221.3  678.95   240.6  679.14   279.1  678.12
   288.7  676.77   298.3  675.16   307.9  672.69   317.6  668.24   336.8   660.8
   394.5  651.77   414.2   649.9   453.5   649.7   532.2  646.06   551.9  645.64
   561.7  646.25   581.4  648.14   787.9  655.24   797.8  656.05   807.6   659.5
   817.4  665.99   846.9   690.1   856.8  697.66   866.6  704.06   886.2   713.4
#Mann= 3 , 0 , 0
       0     .06       0   532.2    .045       0   561.7    .055       0
#XS Ineff= 2 , 0
          487.57  653.99
Permanent Ineff=
       F       F
Bank Sta=532.2,561.7
XS Rating Curve= 0 ,0
Exp/Cntr=0.3,0.1

Type RM Length L Ch R = 1 ,18662.9 ,48.7,48.4,48.7
XS GIS Cut Line= 4
     1465863.933      311914.959      1465774.09      312260.011
     1465732.423      312381.104     1465645.183      312668.865
#Sta/Elev= 30
       0  702.33    28.9  700.85    57.8  697.71    67.5  695.93    77.1  692.93
   134.9  669.41   163.8  661.71   183.1   658.3   298.7  651.24     318  651.09
   346.9  651.76   402.3  649.97   411.4  648.52   420.6  645.84   429.7  643.74
     448  644.39   457.2  645.68   475.5  649.61   484.6     651   494.3  651.44
   523.4  650.76   562.2     651   620.4   652.8   668.9  653.52   707.7  654.99
   736.8  657.87   756.2  659.05   765.9  661.27   775.6  667.99   785.3  677.51
#Mann= 3 , 0 , 0
       0    .055       0   420.6    .045       0     448    .055       0
#XS Ineff= 2 , 0
          385.34  653.01
Permanent Ineff=
       F       F
Bank Sta=420.6,448
XS Rating Curve= 0 ,0
Exp/Cntr=0.3,0.1

Type RM Length L Ch R = 1 ,18614.5 ,358.9,351.5,339.4
XS GIS Cut Line= 4
     1465781.902       312034.75      1465724.61      312260.011
     1465682.944      312381.104     1465595.704      312668.865
#Sta/Elev= 30
       0   687.2    19.4  677.39      29  673.24    38.7  669.92    67.8  661.47
    77.5   659.4    87.2  657.92   125.9  654.03   145.3  652.75     155  652.58
   193.7  654.45     269  655.54   278.2  653.27   287.3  648.61   296.5  644.91
   305.6  643.82   314.8  644.46   323.9   645.6   351.4  650.62   360.5  651.68
   370.2  651.92     409   651.2   486.6  651.09   544.8  652.39   573.9  654.23
   622.4  660.29   632.1  661.02   641.8  662.48   651.5  667.98   661.2  676.82
#Mann= 3 , 0 , 0
       0     .05       0   287.3    .045       0   323.9     .06       0
Bank Sta=287.3,323.9
XS Rating Curve= 0 ,0
Exp/Cntr=0.3,0.1

Type RM Length L Ch R = 1 ,18263   ,257.7,258.1,256.7
XS GIS Cut Line= 3
     1465421.225      312021.729     1465512.371      312506.104
      1465555.34      312694.907
#Sta/Elev= 30
       0   688.7     9.7  683.16    19.3  678.26      29  674.45    38.7  671.62
     116  653.05   125.6  651.05   135.3  649.94   299.6  648.51   376.9  648.26
   415.6  648.36   454.2  649.45   473.6  649.44   492.9  647.67   512.2   644.5
   521.9  643.09   531.6  642.66   541.3  644.09   560.6   649.4   589.7  658.32
   599.4  660.36     609  661.28   618.7  661.57   628.4  662.86   638.1   666.5
   647.8  672.28   657.5  679.17   667.1  686.62   676.8  694.88   686.5  703.77
#Mann= 3 , 0 , 0
       0     .05       0   512.2    .045       0   541.3     .08       0
#XS Ineff= 2 , 0
          315.18  653.96
Permanent Ineff=
       F       F
Bank Sta=512.2,541.3
XS Rating Curve= 0 ,0
Exp/Cntr=0.3,0.1

Type RM Length L Ch R = 1 ,18005   ,229.2,222.1,216.6
XS GIS Cut Line= 3
     1465216.798      312127.198     1465281.034      312319.907
     1465343.534      312641.087
#Sta/Elev= 30
       0   665.4    19.4  661.19      29  659.47    38.7  658.05      58  656.09
    87.1  654.54   135.4  652.47   183.8  651.66     232  650.24   251.2  648.09
  285.01643.0375   289.8  642.44   299.4  641.96  312.72  642.46   318.6  642.95
   337.9  645.47   347.5  645.92   366.7  646.14   376.4  647.71     386  650.59
   414.8  660.15   424.5  662.96   434.1  664.74   453.4  666.51     463  668.61
   472.6  671.39   482.2  673.57   491.8   674.5   511.1  675.78   530.3  677.74
#Mann= 3 , 0 , 0
       0     .08       0  285.01    .045       0  312.72      .1       0
Bank Sta=285.01,312.72
XS Rating Curve= 0 ,0
Exp/Cntr=0.3,0.1

Type RM Length L Ch R = 1 ,17782.9 ,301.7,288.5,275.5
XS GIS Cut Line= 3
     1464978.951       312318.17     1465058.812      312401.504
     1465234.159      312694.907
#Sta/Elev= 30
       0  710.54    19.2  704.95    38.5  698.72    48.1  695.18    57.7  690.96
    67.3  686.13      77  680.14    86.6  672.76    96.2   664.3   105.8  656.96
   115.4   653.2   144.7  648.87   164.2  647.15  178.94  643.12   183.8  641.93
   193.6  641.42   203.3  642.66   213.1  644.54   222.8  645.43   291.2  646.14
   310.7  647.19   320.5   649.1   330.3  651.91     340  654.12   349.8  655.02
   359.6   656.6   388.9  668.75   398.6  671.05   418.2  672.56   457.2  674.18
#Mann= 3 , 0 , 0
       0      .1       0  178.94    .045       0   203.3      .1       0
Bank Sta=178.94,203.3
XS Rating Curve= 0 ,0
Exp/Cntr=0.3,0.1

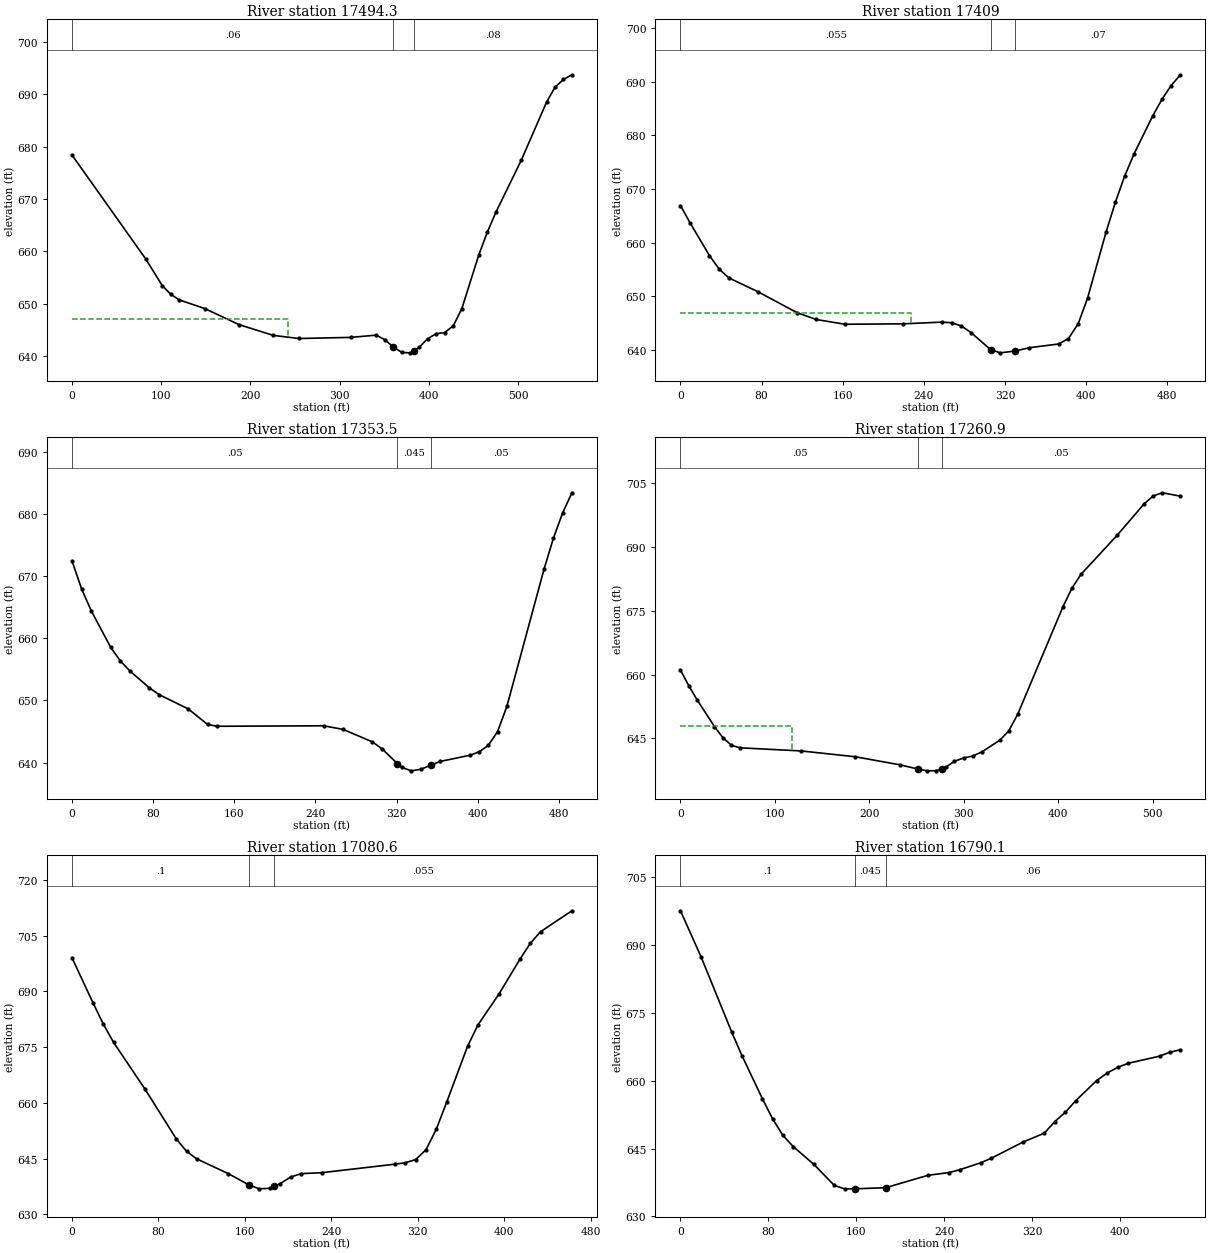
Type RM Length L Ch R = 1 ,17494.3 ,89.8,85.4,80.5
XS GIS Cut Line= 4
     1464565.756      312542.129     1464673.395      312566.434
     1464975.478      312714.004     1465069.228       312778.24
#Sta/Elev= 30
       0  678.39    82.8  658.49   101.2  653.42   110.4  651.83     120  650.72
   148.8  649.05   187.2  645.98   225.6  643.92   254.4  643.33   312.1  643.54
   340.9  643.97   350.5   643.1   360.1  641.71   369.7  640.66   379.3  640.59
  382.78640.9634   388.9  641.62   398.5  643.29   408.1  644.25   417.7  644.46
   427.3  645.77   436.9  649.06     456  659.38   465.5  663.69     475  667.45
   503.4  677.37   531.8   688.5   541.2  691.33   550.7  692.82   560.2  693.72
#Mann= 3 , 0 , 0
       0     .06       0   360.1    .045       0  382.78     .08       0
#XS Ineff= 2 , 0
          241.88  647.05
Permanent Ineff=
       F       F
Bank Sta=360.1,382.78
XS Rating Curve= 0 ,0
Exp/Cntr=0.3,0.1

Type RM Length L Ch R = 1 ,17409   ,54.9,55.5,56.5
XS GIS Cut Line= 4
     1464551.867      312681.018     1464803.603      312736.573
     1464933.812      312769.559      1465032.77      312788.657
#Sta/Elev= 30
       0  666.92     9.6  663.64    28.6  657.58    38.2  655.06    47.7  653.42
    76.4  650.85   114.6  646.97   133.7  645.67   162.3  644.78   219.6  644.86
   257.8  645.18   267.4  645.06     277  644.46   286.6  643.21   305.8  640.04
   315.4  639.45  329.36639.7698   344.1  640.41   372.9   641.1   382.5  642.11
   392.1  644.87   401.3  649.62   419.6  661.97   428.8  667.55   437.9   672.4
   447.1  676.52   465.4  683.58   474.6   686.7   483.7   689.3   492.9  691.31
#Mann= 3 , 0 , 0
       0    .055       0   305.8    .045       0  329.36     .07       0
#XS Ineff= 2 , 0
          227.75  646.83
Permanent Ineff=
       F       F
Bank Sta=305.8,329.36
XS Rating Curve= 0 ,0
Exp/Cntr=0.3,0.1

Type RM Length L Ch R = 1 ,17353.5 ,99.6,92.6,84.8
XS GIS Cut Line= 4
     1464534.506      312731.365     1464786.242       312786.92
     1464916.451      312819.907     1465015.409      312839.004
#Sta/Elev= 30
       0  672.44     9.6  667.89    19.1  664.38    38.2  658.53    47.7  656.34
    57.3   654.7    76.4     652    85.9  650.92   114.6  648.63   133.7  646.12
   143.2  645.83   248.2  645.91   267.4  645.32   296.2  643.32   305.8  642.19
  320.86639.8237     325  639.22   334.6  638.66   344.1  638.92   353.7  639.56
   363.3  640.18   392.1  641.16   401.3   641.7   410.4  642.74   419.6  644.98
   428.8  649.04   465.4   671.1   474.6  676.06   483.7  680.15   492.9   683.4
#Mann= 3 , 0 , 0
       0     .05       0  320.86    .045       0   353.7     .05       0
Bank Sta=320.86,353.7
XS Rating Curve= 0 ,0
Exp/Cntr=0.3,0.1

Type RM Length L Ch R = 1 ,17260.9 ,185.2,180.3,175.4
XS GIS Cut Line= 4
     1464614.367      312929.282     1464709.853       312903.24
     1464958.117      312892.823     1465136.937      312925.809
#Sta/Elev= 30
       0  661.03       9  657.28      18  653.89      36  647.74      45  645.08
      54  643.33      63  642.73   127.6     642     185  640.63   232.8  638.71
   251.9   637.7   261.4  637.31     271  637.34  276.37637.7745   280.6  638.12
   290.1  639.56   299.7  640.34   309.2  640.78   318.8  641.73   337.9   644.5
   347.5  646.69     357  650.62   404.9  675.93   414.4  680.31     424  683.58
   462.3  692.79     491  700.22   500.6  702.07   510.2   702.8   529.3     702
#Mann= 3 , 0 , 0
       0     .05       0   251.9    .045       0  276.37     .05       0
#XS Ineff= 2 , 0
          118.32  647.92
Permanent Ineff=
       F       F
Bank Sta=251.9,276.37
XS Rating Curve= 0 ,0
Exp/Cntr=0.3,0.1

Type RM Length L Ch R = 1 ,17080.6 ,287.3,290.5,293.2
XS GIS Cut Line= 3
     1464735.895      313118.518     1465043.187       313036.92
     1465187.284      313024.768
#Sta/Elev= 30
       0  699.08    19.3  687.03    28.9  681.29    38.5   676.3    67.4   663.8
    96.4  650.39     106  646.98   115.6  644.92   144.5  641.01   163.8  637.93
   173.4  636.89   183.1  637.04  186.82637.5282   192.7   638.3   202.3  640.05
     212  640.98   231.2  641.24   298.7  643.52   308.3   643.9   317.9  644.75
   327.6  647.42   337.2     653   346.9  660.36   366.1   675.3   375.8  681.07
   395.1  689.32   414.4  698.63     424  702.93   433.6  706.09   462.6  711.72
#Mann= 3 , 0 , 0
       0      .1       0   163.8    .045       0  186.82    .055       0
Bank Sta=163.8,186.82
XS Rating Curve= 0 ,0
Exp/Cntr=0.3,0.1

Type RM Length L Ch R = 1 ,16790.1 ,204.8,220.7,237
XS GIS Cut Line= 4
     1464836.156      313367.216     1465011.926      313344.412
     1465164.281      313322.945     1465265.409      313394.559
#Sta/Elev= 30
       0  697.57    18.7  687.41    46.6  670.78      56  665.52    74.6     656
      84   651.5    93.3   647.9   102.6  645.44   121.3  641.53   139.9  636.88
   149.3   636.1   158.6   636.1   186.9  636.36   225.3   639.1   244.6   639.7
   254.2  640.33   273.4  641.87     283  642.88   311.9  646.46   331.1   648.4
   340.6  650.95   350.2  653.01   359.7  655.58   378.8  660.04   388.3   661.7
   397.8  662.94   407.4  663.85     436  665.43   445.5   666.3     455  666.85
#Mann= 3 , 0 , 0
       0      .1       0   158.6    .045       0   186.9     .06       0
Bank Sta=158.6,186.9
XS Rating Curve= 0 ,0
Exp/Cntr=0.3,0.1

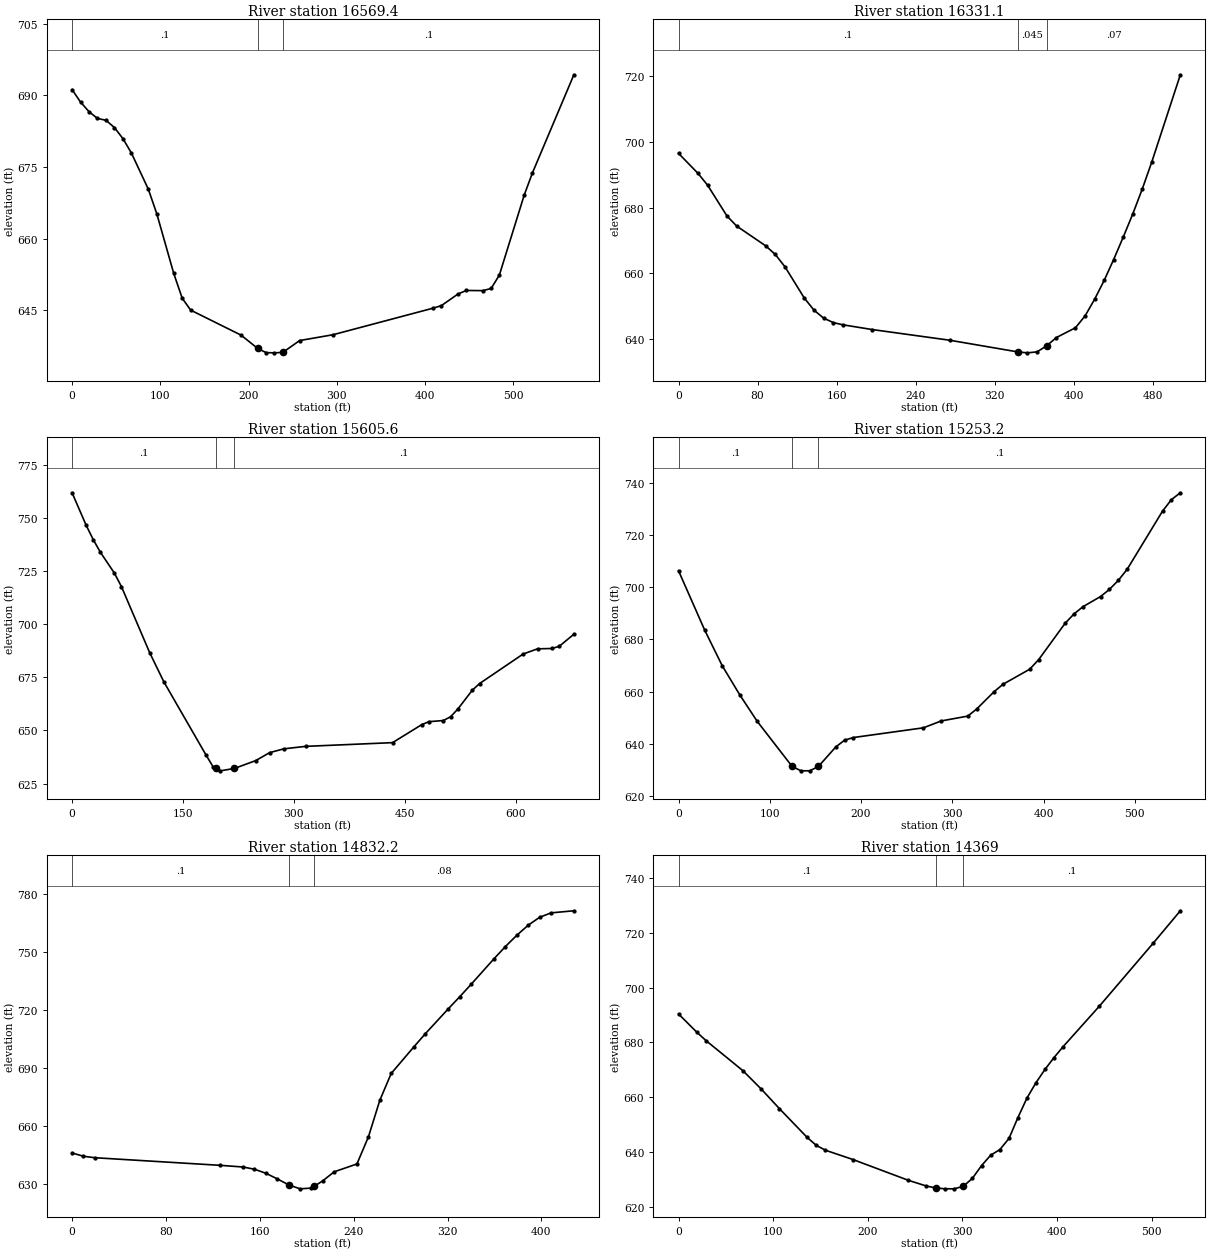
Type RM Length L Ch R = 1 ,16569.4 ,218.1,238.3,258.4
XS GIS Cut Line= 4
     1464846.572      313408.882     1464940.322      313518.257
     1465138.239      313648.466     1465298.395      313746.122
#Sta/Elev= 30
       0  691.18     9.6  688.57    19.2  686.56    28.8  685.15    38.4  684.76
      48  683.24    57.6  680.93    67.2  677.92    86.4  670.34      96   665.2
   115.2  652.71   124.8  647.53   134.4  645.04   191.4  639.82   210.4  637.02
   219.9  636.15   229.3  636.11   238.8   636.2   257.8  638.68   295.7   639.9
   409.1  645.46   418.5     646   437.2  648.41   446.6  649.16   465.4  649.12
   474.8  649.58   484.1  652.38   512.3  669.14   521.6  673.77   568.5  694.28
#Mann= 3 , 0 , 0
       0      .1       0   210.4    .045       0   238.8      .1       0
Bank Sta=210.4,238.8
XS Rating Curve= 0 ,0
Exp/Cntr=0.3,0.1

Type RM Length L Ch R = 1 ,16331.1 ,741.8,725.5,709.1
XS GIS Cut Line= 4
     1464812.718      313399.768     1464860.895      313579.455
     1464881.728      313774.768     1464890.843      313899.768
#Sta/Elev= 30
       0  696.47    19.6  690.43    29.4  686.81      49  677.46    58.8   674.4
    88.1  668.41    97.9  665.78   107.7  662.03   127.3  652.52   137.1  648.86
   146.9  646.42   156.7  645.08   166.4  644.41   195.8  642.98   274.4  639.73
   343.2  636.19     353   635.9   362.8  636.19   372.6  638.06   382.4  640.55
   401.7  643.52   411.4  647.12     421  652.13   430.7  657.87   440.3  664.21
   449.9  670.95   459.6  678.01   469.2  685.57   478.9  693.84   507.8  720.33
#Mann= 3 , 0 , 0
       0      .1       0   343.2    .045       0   372.6     .07       0
Bank Sta=343.2,372.6
XS Rating Curve= 0 ,0
Exp/Cntr=0.3,0.1

Type RM Length L Ch R = 1 ,15605.6 ,377.1,352.5,327.8
XS GIS Cut Line= 3
     1464101.781      313356.799     1464311.416      313552.111
     1464608.291      313808.622
#Sta/Elev= 30
       0  761.77    19.1  746.47    28.6  739.77    38.2  733.86    57.3  723.96
    66.8  717.64   105.1  686.49   124.2  672.84   181.5  638.27     191  632.77
  194.37632.1441   200.6  630.99   219.7  632.13   248.3  635.78   267.4  639.56
   286.5  641.34     316   642.5   433.6  644.25   472.9  652.68   482.7  654.11
   502.3  654.65   512.1  656.42   521.9  660.04   541.5  668.91   551.4  672.06
   610.2  685.92   629.8  688.38   649.4  688.53   659.2  689.58   678.9  695.24
#Mann= 3 , 0 , 0
       0      .1       0  194.37    .045       0   219.7      .1       0
Bank Sta=194.37,219.7
XS Rating Curve= 0 ,0
Exp/Cntr=0.3,0.1

Type RM Length L Ch R = 1 ,15253.2 ,402.3,421,439.1
XS GIS Cut Line= 3
     1464173.395      313862.007     1464416.885      313774.768
     1464674.697      313910.184
#Sta/Elev= 30
       0  706.35    28.7  683.55    47.9  669.89    67.1  658.74    86.2  648.58
   124.5  631.26   134.1  629.61   143.7  629.58   153.3  631.26   172.4  638.78
     182  641.35   191.6  642.36   268.4  646.09   287.8  648.72   316.9  650.58
   326.6  653.26     346  660.01   355.7  662.82   384.8  668.56   394.6  672.22
   423.7  686.22   433.4  689.78   443.1  692.53   462.5  696.47   472.2  699.19
   481.9  702.64   491.6  706.89   530.4  729.23   540.2  733.66   549.9  736.27
#Mann= 3 , 0 , 0
       0      .1       0   124.5    .045       0   153.3      .1       0
Bank Sta=124.5,153.3
XS Rating Curve= 0 ,0
Exp/Cntr=0.3,0.1

Type RM Length L Ch R = 1 ,14832.2 ,446.7,463.3,479.5
XS GIS Cut Line= 3
     1464308.812      314087.268     1464524.958      314197.945
     1464672.093      314309.924
#Sta/Elev= 30
       0  645.85     9.7  644.16    19.4   643.4   126.3  639.46   145.7   638.6
   155.4  637.45   165.1  635.39   174.8  632.48   184.6  629.37   194.3   627.3
     204   627.7  206.27628.5776   213.7  631.45   223.4  636.11   242.8  640.17
   252.6   654.2   262.3  673.08     272  686.99   291.5  700.88   301.2  707.63
   320.7  720.46   330.4  726.67   340.2  733.17   359.6  746.32   369.3  752.64
   379.1  758.51   388.8  763.72   398.5  767.79   408.3  770.09   427.7  771.17
#Mann= 3 , 0 , 0
       0      .1       0   184.6    .045       0  206.27     .08       0
Bank Sta=184.6,206.27
XS Rating Curve= 0 ,0
Exp/Cntr=0.3,0.1

Type RM Length L Ch R = 1 ,14369   ,587.7,603.8,619.5
XS GIS Cut Line= 3
     1464049.697      314214.872     1464173.046      314531.321
     1464243.708      314708.361
#Sta/Elev= 30
       0  690.35    19.4  683.65    29.1   680.6    67.9  669.67    87.3  662.96
   106.7  655.74   135.9  645.26   145.6  642.35   155.3  640.57   184.4  637.17
   242.6  629.62     262  627.49   271.7   626.8   281.4  626.49   291.1  626.47
   300.8  627.36   310.5  630.28   320.2  634.94   329.9  638.77   339.6  640.81
   349.2  644.86   358.7  652.52   368.2  659.62   377.8  665.27   387.3  670.11
   396.8  674.42   406.4  678.39   444.5   693.1   501.7  716.23   530.3  728.04
#Mann= 3 , 0 , 0
       0      .1       0   271.7    .045       0   300.8      .1       0
Bank Sta=271.7,300.8
XS Rating Curve= 0 ,0
Exp/Cntr=0.3,0.1

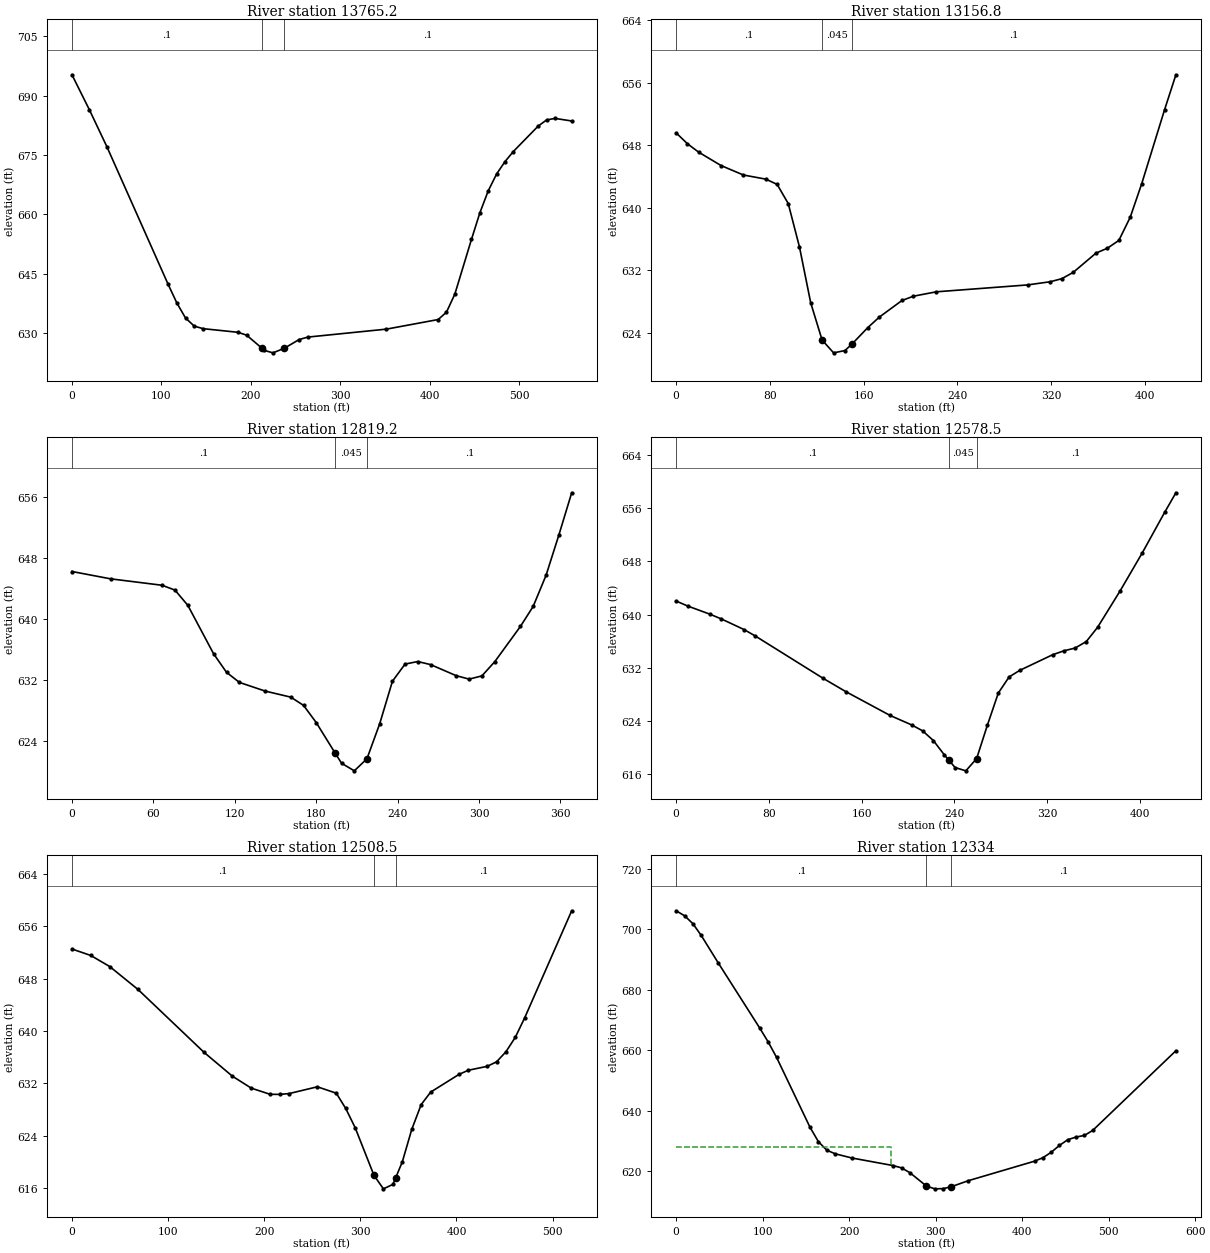
Type RM Length L Ch R = 1 ,13765.2 ,623.3,608.4,593.1
XS GIS Cut Line= 4
     1463599.176      314360.705     1463618.708      314496.122
     1463534.072      314735.705     1463592.666      314893.257
#Sta/Elev= 30
       0  695.29    19.6   686.4    39.1   677.1   107.5  642.39   117.3  637.66
     127  633.85   136.8   631.8   146.6  631.16   185.7  630.24   195.4  629.51
  212.28626.2629     215  625.68   224.8  625.05  237.42626.1887   254.1  628.41
   263.9  629.03   351.8  631.04   409.6  633.46   418.9  635.31   428.3  639.89
   446.9  653.72   456.3  660.43   465.6  665.95     475  670.23   484.3  673.33
   493.6  675.88   521.6  682.35     531  683.89   540.3  684.27     559  683.62
#Mann= 3 , 0 , 0
       0      .1       0  212.28    .045       0  237.42      .1       0
Bank Sta=212.28,237.42
XS Rating Curve= 0 ,0
Exp/Cntr=0.3,0.1

Type RM Length L Ch R = 1 ,13156.8 ,321.2,337.6,353.6
XS GIS Cut Line= 3
     1462968.968      314591.174     1463014.541      314696.643
     1463121.312      314989.611
#Sta/Elev= 30
       0  649.57     9.6  648.19    19.2  647.11    38.3   645.4    57.4  644.19
    76.6  643.66    86.2  642.99    95.7  640.54   105.3  634.98   114.9  627.84
   124.6   623.1   134.4  621.46   144.1  621.75  150.03622.5685   163.6  624.68
   173.4  626.02   192.8  628.15   202.6   628.7   222.1  629.26     300  630.14
   319.5  630.55   329.3  630.94     339  631.74   358.5  634.21   368.2  634.83
     378  635.83   387.7  638.79   397.5  643.07     417  652.52   426.7     657
#Mann= 3 , 0 , 0
       0      .1       0   124.6    .045       0  150.03      .1       0
Bank Sta=124.6,150.03
XS Rating Curve= 0 ,0
Exp/Cntr=0.3,0.1

Type RM Length L Ch R = 1 ,12819.2 ,222.9,240.7,258.3
XS GIS Cut Line= 4
     1462837.458      314709.664     1462765.843      314854.195
     1462731.989      314941.434     1462690.322      315046.903
#Sta/Elev= 30
       0  646.21    28.5  645.25    66.4  644.41    75.9  643.78    85.4  641.78
   104.4  635.44   113.9  633.02   123.4   631.7   142.3  630.57   161.3  629.77
   170.7  628.69     180  626.45  194.09622.4138   198.7  621.12   208.1  620.13
   217.4  621.71   226.8  626.29   236.2  631.86   245.5   634.1   254.9  634.43
   264.3  634.03   283.2  632.58   292.7  632.13   302.1  632.55   311.6  634.41
   330.5  639.02   339.9  641.64   349.4  645.71   358.8  650.96   368.3  656.51
#Mann= 3 , 0 , 0
       0      .1       0  194.09    .045       0   217.4      .1       0
Bank Sta=194.09,217.4
XS Rating Curve= 0 ,0
Exp/Cntr=0.3,0.1

Type RM Length L Ch R = 1 ,12578.5 ,82.2,69.9,57.7
XS GIS Cut Line= 4
      1462782.77      314686.226     1462623.916      314734.403
     1462488.499      314796.903     1462422.093      314891.955
#Sta/Elev= 30
       0  642.05     9.8  641.31    29.3  640.06    39.1  639.35    58.6  637.76
    68.4  636.78   126.9  630.42   146.5  628.42   184.6  624.85   203.3  623.42
   212.6  622.54   221.9  621.08   231.2  618.96  235.39618.0997   240.6  617.03
   249.9  616.53   259.2  618.37   268.5   623.4   277.9  628.22   287.2  630.64
   296.5  631.64   324.8  633.98   334.5  634.57   344.1  634.98   353.8  635.96
   363.5  638.09   382.8  643.52   402.1  649.29   421.4  655.38   431.1  658.32
#Mann= 3 , 0 , 0
       0      .1       0  235.39    .045       0   259.2      .1       0
Bank Sta=235.39,259.2
XS Rating Curve= 0 ,0
Exp/Cntr=0.3,0.1

Type RM Length L Ch R = 1 ,12508.5 ,178.4,174.6,170.3
XS GIS Cut Line= 3
     1462689.454      314455.974     1462460.288      314774.985
     1462387.371      314879.151
#Sta/Elev= 30
       0  652.53    19.6  651.54    39.3  649.85    68.7  646.35   137.5  636.73
   166.9   633.1   186.6  631.27   206.2  630.33     216  630.32   225.8  630.44
   255.3  631.48     275   630.5   284.8  628.17   294.6  625.24   314.2  617.95
     324  615.89   333.9  616.57  336.78617.5839   343.7  620.02   353.5  624.97
   363.3  628.76   373.2  630.67   402.6  633.37   412.4  634.01   431.9   634.6
   441.7  635.29   451.5  636.83   461.3  639.06     471  642.02   519.9  658.37
#Mann= 3 , 0 , 0
       0      .1       0   314.2    .045       0  336.78      .1       0
Bank Sta=314.2,336.78
XS Rating Curve= 0 ,0
Exp/Cntr=0.3,0.1

Type RM Length L Ch R = 1 ,12334   ,332,320.8,309.7
XS GIS Cut Line= 3
     1462448.135      314306.018     1462429.906      314479.195
     1462256.728      314843.778
#Sta/Elev= 30
       0  706.06     9.7  704.41    19.4  701.78      29   697.9    48.4  688.95
    96.7  667.28   106.4  662.73   116.1  657.62   154.8  634.51   164.5  629.76
   174.1  626.99   183.7  625.79     203   624.4     251  621.88   260.6  621.12
   270.2  619.54   289.4  615.11   299.1   614.2   308.7  614.27   318.3  614.91
   337.5  616.87   414.4  623.34     424  624.48   433.6  626.27   443.2  628.56
   452.8  630.44   462.4  631.32     472  631.84   481.7  633.52   577.8  659.82
#Mann= 3 , 0 , 0
       0      .1       0   289.4    .045       0   318.3      .1       0
#XS Ineff= 2 , 0
          248.17  627.87
Permanent Ineff=
       F       F
Bank Sta=289.4,318.3
XS Rating Curve= 0 ,0
Exp/Cntr=0.3,0.1

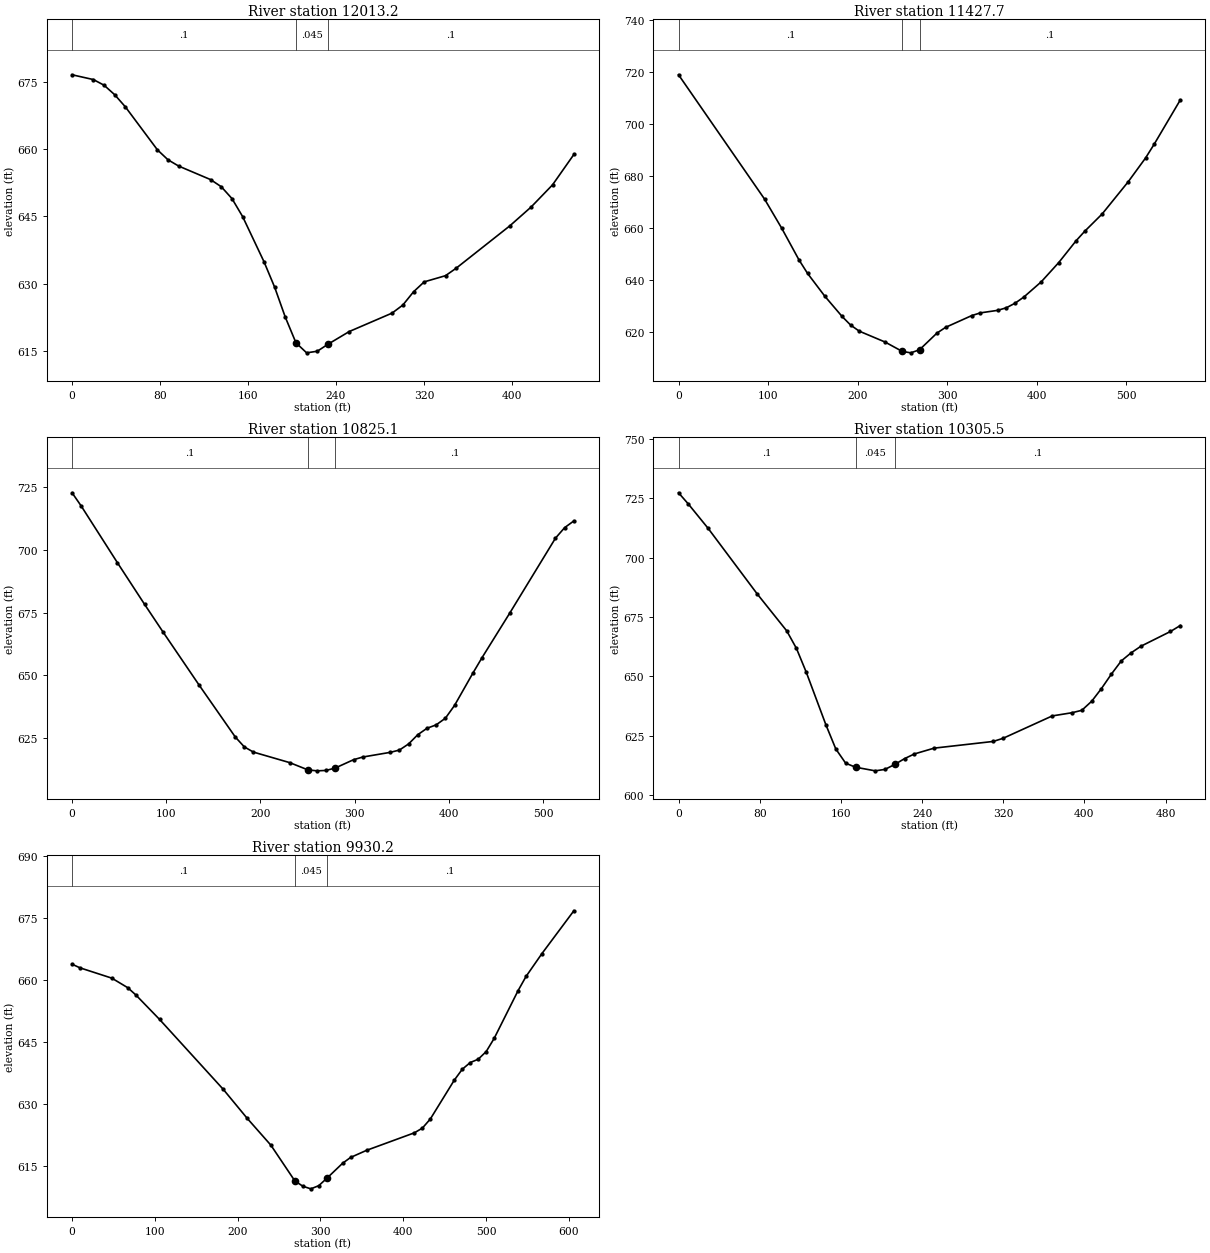
Type RM Length L Ch R = 1 ,12013.2 ,584.5,585.5,587.5
XS GIS Cut Line= 3
     1462056.642      314358.318      1462068.36      314580.974
     1462080.079      314814.047
#Sta/Elev= 30
       0  676.59    19.4  675.52    29.1  674.26    38.8  672.13    48.5  669.42
    77.6  659.84    87.2  657.62    96.9  656.22     126  653.19   135.7   651.6
   145.4  648.96   155.1  644.94   174.5  634.88   184.2  629.19   193.9  622.49
   203.6  616.77   213.3  614.53     223  614.89   232.7  616.45   252.1  619.29
     291   623.4   300.8   625.2   310.5  628.15   320.2  630.37   339.6  631.75
   349.4  633.44     398  642.86   417.4  647.07   436.9  652.02   456.3   658.8
#Mann= 3 , 0 , 0
       0      .1       0   203.6    .045       0   232.7      .1       0
Bank Sta=203.6,232.7
XS Rating Curve= 0 ,0
Exp/Cntr=0.3,0.1

Type RM Length L Ch R = 1 ,11427.7 ,607.6,602.6,595.4
XS GIS Cut Line= 3
      1461492.84       314384.36     1461495.951       314643.63
     1461485.027      314944.256
#Sta/Elev= 30
       0  718.85      96  671.07   115.2  659.84   134.4  647.72     144   642.5
   163.3  633.72   182.5  625.96   192.1  622.63   201.7   620.3   230.5  616.12
   249.7  612.51   259.3  611.96     269  613.15   288.4  619.54   298.1  621.76
   327.2  626.27   336.9  627.32   356.3   628.3     366   629.3   375.7  631.05
   385.4   633.4   404.8  639.24   424.3  646.63   443.7  655.02   453.4   658.7
   472.8  665.33   501.9  677.71   521.3  686.87     531  692.21   560.1  709.19
#Mann= 3 , 0 , 0
       0      .1       0   249.7    .045       0     269      .1       0
Bank Sta=249.7,269
XS Rating Curve= 0 ,0
Exp/Cntr=0.3,0.1

Type RM Length L Ch R = 1 ,10825.1 ,522.7,519.6,517
XS GIS Cut Line= 3
     1460844.402      314448.162     1460908.374      314710.061
     1460982.423      314962.485
#Sta/Elev= 30
       0  722.88     9.6  717.66    48.1     695      77  678.35    96.3  667.47
   134.8  646.18   173.3  625.41   182.9  621.46   192.6  619.39   231.1  615.19
   250.3  612.31     260  611.92   269.6  612.08   279.3  613.03   298.8  616.36
   308.6  617.43   337.8   619.3   347.5  620.21   357.3  622.67     367  626.34
   376.8  628.91   386.5  630.26   396.3  632.91     406     638   425.5  650.91
   435.2  657.08   464.5  674.78   513.2  704.78   522.9  708.96   532.7  711.65
#Mann= 3 , 0 , 0
       0      .1       0   250.3    .045       0   279.3      .1       0
Bank Sta=250.3,279.3
XS Rating Curve= 0 ,0
Exp/Cntr=0.3,0.1

Type RM Length L Ch R = 1 ,10305.5 ,380.4,375.4,370.4
XS GIS Cut Line= 3
     1460337.892      314622.641     1460434.727      314865.627
     1460550.131      315067.953
#Sta/Elev= 30
       0  727.32     9.7  722.57    29.1  712.36    77.5   684.7   106.6  669.13
   116.2  661.72   125.9  651.66   145.3  629.44     155  619.33   164.7  613.34
   174.4  611.65   193.8  610.12   203.4  610.72   213.1  612.82   222.8  615.28
   232.5  617.25   251.9  619.69   310.1  622.51   319.8  623.83   368.3  633.27
   387.7  634.61   397.4  635.63   407.2  639.47   416.8  644.82   426.6  650.91
   436.3  656.44     446  659.85   455.7  662.65   484.8  668.86   494.5  671.37
#Mann= 3 , 0 , 0
       0      .1       0   174.4    .045       0   213.1      .1       0
Bank Sta=174.4,213.1
XS Rating Curve= 0 ,0
Exp/Cntr=0.3,0.1

Type RM Length L Ch R = 1 ,9930.2  ,9928.8,9930.3,9921.4
XS GIS Cut Line= 3
     1460073.569      314733.318     1460065.756      314963.787
     1460277.996      315273.683
#Sta/Elev= 30
       0  663.86     9.6  662.98      48  660.49    67.3  658.17    76.9  656.45
   105.7   650.5   182.6  633.59   211.4   626.6   240.2  620.06   269.1  611.43
   278.8  610.13   288.4   609.5     298  610.26   307.6  612.02   326.9   615.7
   336.5   617.1   355.8  618.82   413.6  623.06   423.2   624.2   432.8   626.4
   461.7  635.79   471.4  638.44     481  640.06   490.6  640.86   500.3  642.72
   509.9   645.9   538.8  657.46   548.4  660.89   567.7  666.45   606.2  676.79
#Mann= 3 , 0 , 0
       0      .1       0   269.1    .045       0   307.6      .1       0
Bank Sta=269.1,307.6
XS Rating Curve= 0 ,0
Exp/Cntr=0.3,0.1

Chan Stop Cuts=-1
Use User Specified Reach Order=0
Composite Channel Slope=5